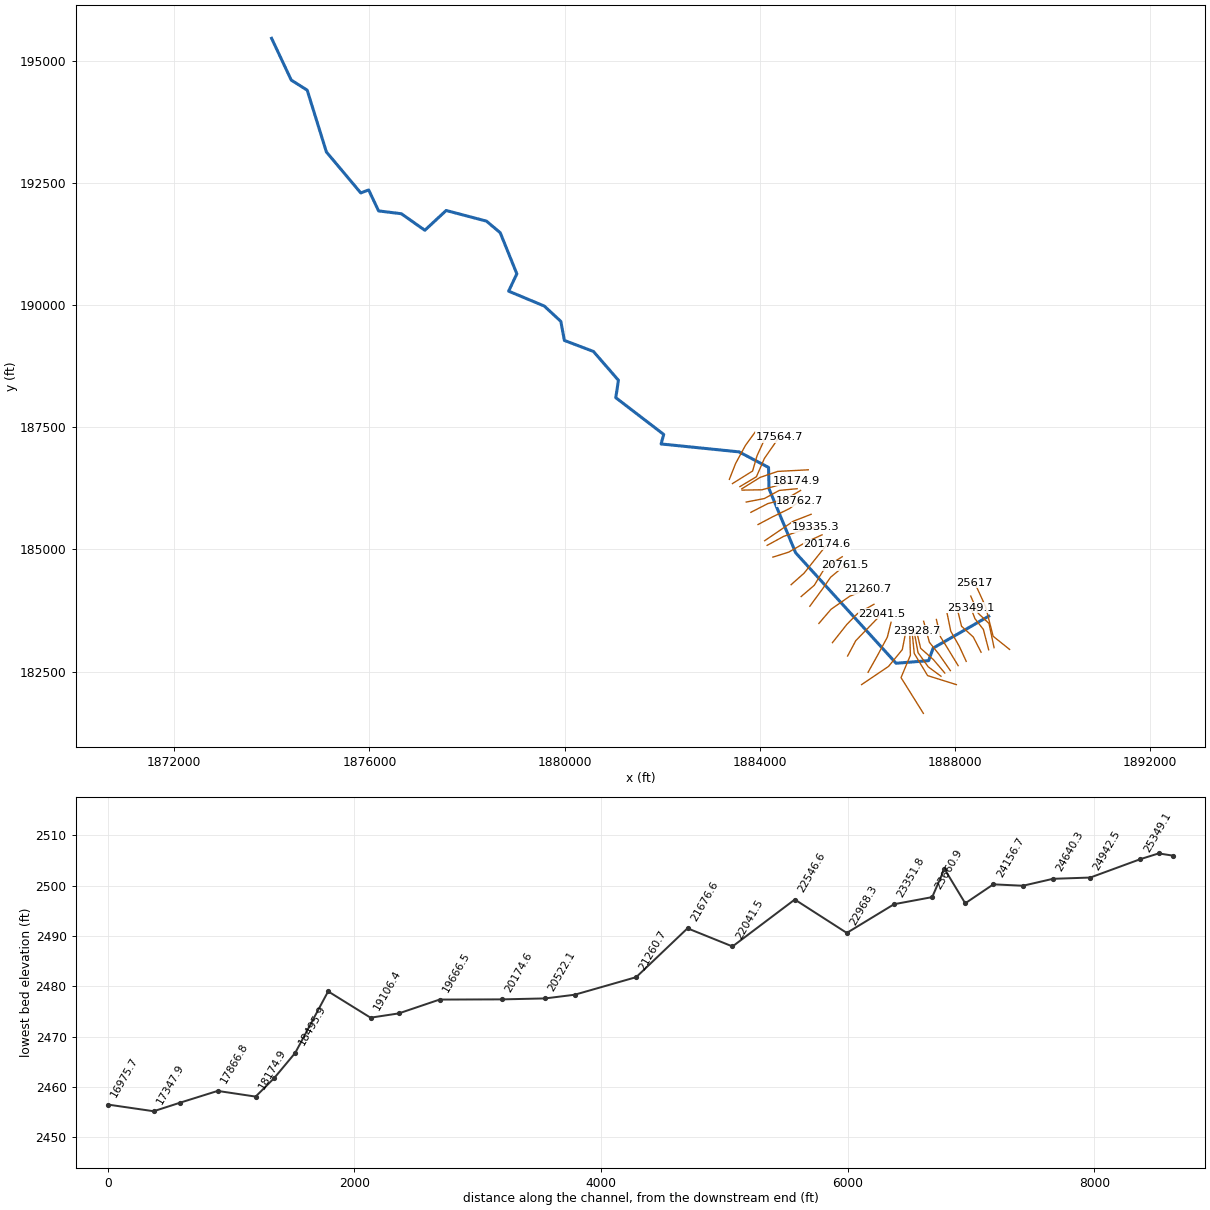
--- MilamFk2.prj (project) ---

Proj Title=MilamFk2
Current Plan=p01
Default Exp/Contr=0,0
English Units
Geom File=g01
Flow File=f01
Plan File=p01
BEGIN DESCRIPTION:
END DESCRIPTION:
DSS Export Rating Curves= 0
DSS Export Rating Curve Sorted= 0
DSS Export Volume Flow Curves= 0
DXF OffsetX= 0
DXF OffsetY= 0
DXF ScaleX= 0
DXF ScaleY= 0

--- MilamFk2.p01 (plan) ---

Plan Title=Floodplain
Program Version=4.00
Geom File=g01
Flow File=f01
K Sum by GR=0
Std Step Tol=0.01
Critical Tol=0.01
Num of Std Step Trials=20
Max Error Tol=0.3
Flow Tol Ratio=0.001
Split Flow NTrial=30
Split Flow Tol=0.02
Split Flow Ratio=0.02
Log Output Level=0
Friction Slope Method=1
Unsteady Friction Slope Method=2
Unsteady Bridges Friction Slope Method=1
Global Log Level=0
CheckData=False
Run HTab=0
Run UNet=0
Run PostProcess=0
UNET Theta=0
UNET Theta Warmup=0
UNET ZTol=0
UNET ZSATol=0
UNET MxIter=0
UNET MaxInSteps=0
UNET DtIC=0
UNET DtMin=0
UNET MaxCRTS=0
UNET WFStab=0
UNET SFStab=0
UNET WFX=0
UNET SFX=0
UNET DSS MLevel=0
UNET DZMax Abort=0
UNET Convert EG Bridges=0
UNET Use Existing IB Tables=0
UNET Froude Limit=0
UNET Froude Power=0
Write IC File=0
Echo Input=False
Echo Output=False
Write Detailed=0

--- MilamFk2.f01 (steady flow) ---

Flow Title=NFF Regression Equation
Program Version=4.00
Number of Profiles=1
Profile Names=P100yr
River Rch & RM=MilamFk2,Main      ,25617
548.7863
River Rch & RM=MilamFk2,Main      ,25497.1
733.5093
River Rch & RM=MilamFk2,Main      ,23351.8
763.2336
River Rch & RM=MilamFk2,Main      ,22968.3
913.0301
River Rch & RM=MilamFk2,Main      ,20761.5
946.8974
River Rch & RM=MilamFk2,Main      ,17866.8
1027.085
River Rch & RM=MilamFk2,Main      ,17564.7
1126.272
River Rch & RM=MilamFk2,Main      ,15160.8
1190.587
River Rch & RM=MilamFk2,Main      ,10226.7
1276.466
River Rch & RM=MilamFk2,Main      ,9599.6
1395.845
River Rch & RM=MilamFk2,Main      ,6750.9
1469.711
River Rch & RM=MilamFk2,Main      ,304
1593.289
River Rch & RM=MilamFk2,Main      ,40.5
2642.050
Boundary for River Rch & Prof#=MilamFk2,Main      ,1
Up Type=0
Dn Type=3
Dn Slope=0.065106

--- MilamFk2.g01 (geometry) ---

Geom Title=USGS 10m DEM
Program Version=4.00

River Reach=MilamFk2        ,Main
Reach XY= 30
      1888691.26      183632.195     1887552.302      182978.915
     1887459.526      182721.998     1886792.844      182669.579
     1884735.013      184929.504     1884188.785      186240.203
     1884179.196      186676.846     1883574.913      186995.363
     1881976.778      187157.305     1882030.633      187352.365
      1881048.25      188104.492     1881102.538       188460.87
     1880590.287      189050.393      1879994.63      189276.121
     1879922.025      189666.269      1879583.36      189979.734
     1878852.301      190284.817     1879020.333      190639.163
     1878679.916      191480.193     1878397.832      191717.875
     1877571.604      191935.532     1877134.956      191530.763
     1876653.088      191869.364     1876187.301      191926.826
     1875983.574      192356.047     1875821.636      192295.103
     1875117.296       193133.52     1874723.771      194397.676
     1874396.414      194604.886     1873994.183      195458.974

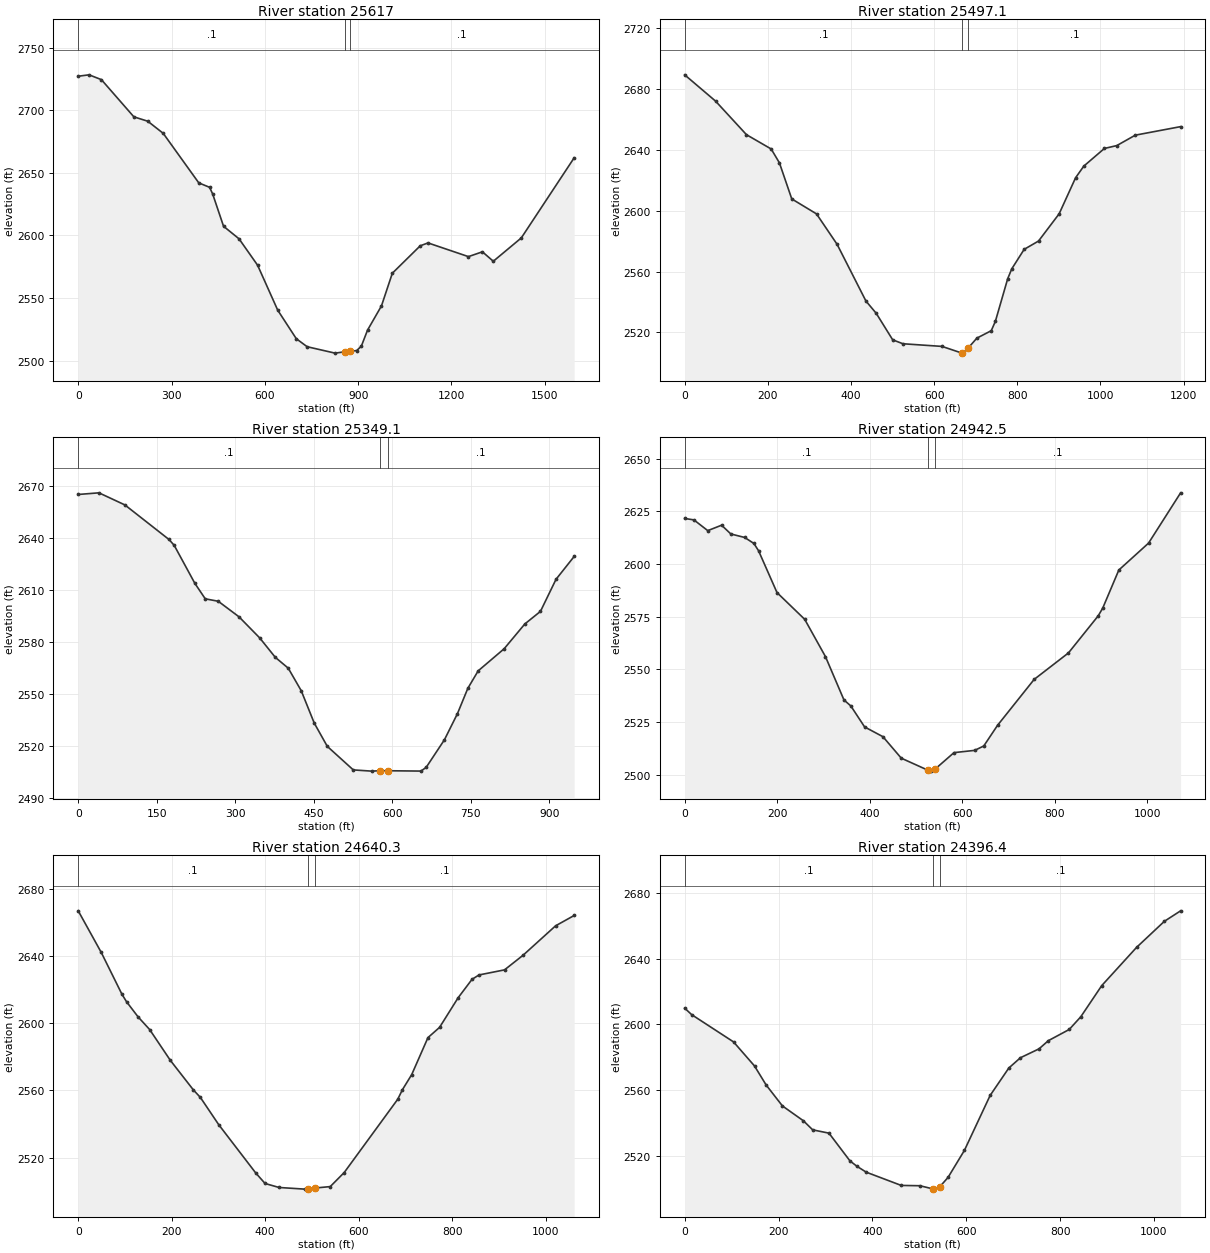
Type RM Length L Ch R = 1 ,25617   ,111.5,119.9,130.9
XS GIS Cut Line= 4
     1889119.571      182951.972     1888781.979      183222.045
     1888626.686      183829.711     1888403.876      184315.843
#Sta/Elev= 30
       0 2727.08    34.8  2728.2    74.5 2724.36   178.9 2694.65   223.6 2691.15
   273.3 2681.46   387.6 2641.91   422.4 2638.36   432.3    2633   467.2 2607.26
     517 2597.24   576.7 2576.14   641.4 2540.24   701.1 2517.46     736 2511.06
   825.6 2505.95   858.1 2507.04   873.1 2507.35   895.3 2508.02   910.2 2511.51
   930.1 2524.33   974.9 2543.68  1009.8 2569.75  1099.5 2591.66  1124.5 2593.96
  1254.4 2583.02  1299.4 2586.86  1334.4 2579.32  1424.4 2597.95  1594.3 2661.92
#Mann= 3 , 0 , 0
       0      .1       0   858.1    .045       0   873.1      .1       0
Bank Sta=858.1,873.1
XS Rating Curve= 0 ,0
Exp/Cntr=0.3,0.1

Type RM Length L Ch R = 1 ,25497.1 ,151.7,148,144.4
XS GIS Cut Line= 4
     1888801.256        182988.7     1888697.167       183483.25
      1888478.19      183690.157     1888322.744      184043.879
#Sta/Elev= 30
       0 2689.38    74.3  2672.1   148.6 2650.04   208.1 2640.62   227.9 2631.51
   257.6  2607.8   317.1 2597.96   366.6 2577.97     436 2540.67   460.8 2532.58
   500.4 2515.15   525.1 2512.57     619 2510.83   667.1 2506.42   668.4 2506.41
   682.1 2509.82   702.9 2516.27   737.5 2521.16   747.4 2527.31     777  2555.3
   786.9 2561.86   816.6 2574.63   851.2  2580.1   900.8 2598.01   940.4 2621.73
   960.2 2629.38  1009.7 2640.98  1039.5 2642.86    1084 2649.71    1193 2655.32
#Mann= 3 , 0 , 0
       0      .1       0   667.1    .045       0   682.1      .1       0
Bank Sta=667.1,682.1
XS Rating Curve= 0 ,0
Exp/Cntr=0.3,0.1

Type RM Length L Ch R = 1 ,25349.1 ,405.9,406.6,390.1
XS GIS Cut Line= 4
      1888690.27      182945.291     1888581.644      183362.554
     1888409.221       183581.53     1888324.734      183803.956
#Sta/Elev= 30
       0 2665.03    39.6 2665.98    89.2    2659   173.5 2639.03   183.4 2635.68
     223 2613.67   242.8 2604.77   267.6 2603.37   307.3 2594.38   346.9 2582.18
   376.6    2571   401.4 2564.72   426.2 2551.71   451.1 2533.01     476 2519.58
   525.7 2505.97   560.6 2505.27   576.6  2505.5   591.6 2505.49   655.1  2505.3
   665.1 2507.48   699.9 2523.38   724.8 2538.48   744.6 2553.08   764.4 2563.18
     814 2575.93   853.6 2590.27   883.4 2597.52   913.1 2616.01   947.8 2629.23
#Mann= 3 , 0 , 0
       0      .1       0   576.6    .045       0   591.6      .1       0
Bank Sta=576.6,591.6
XS Rating Curve= 0 ,0
Exp/Cntr=0.3,0.1

Type RM Length L Ch R = 1 ,24942.5 ,309.3,302.3,295.3
XS GIS Cut Line= 4
     1888535.416      182894.634     1888375.912      183205.462
     1888134.612      183426.313     1888040.545      183810.758
#Sta/Elev= 30
       0 2621.56      20 2620.88    49.9 2615.78    79.8 2618.36    99.8  2614.2
   129.8 2612.53   149.7 2609.68   159.7 2606.25   199.6 2586.38   259.5 2573.68
   304.4 2555.97   344.4  2535.4   359.3 2532.54     389  2522.6   428.7 2517.95
   468.3 2507.76   526.5 2501.99   532.7 2501.61   541.5 2502.59   582.3 2510.39
   626.9 2511.46   646.7 2513.55   676.5 2523.37   755.6 2545.15   829.8 2557.73
   894.2 2575.35     904 2579.05   938.7 2597.08    1003 2609.86  1072.3 2633.73
#Mann= 3 , 0 , 0
       0      .1       0   526.5    .045       0   541.5      .1       0
Bank Sta=526.5,541.5
XS Rating Curve= 0 ,0
Exp/Cntr=0.3,0.1

Type RM Length L Ch R = 1 ,24640.3 ,243,243.9,244.7
XS GIS Cut Line= 4
      1888230.61       182707.93     1888088.398      183016.765
      1887913.76      183324.067     1887840.143      183683.973
#Sta/Elev= 30
       0 2666.81    49.3 2642.06    93.6 2617.18   103.5 2612.71   128.1 2603.75
   152.8 2596.24   197.1  2577.9   246.4 2560.32   261.2 2555.92   300.6 2539.66
   379.8 2510.94   399.7 2504.71   429.6 2502.34   484.4 2501.36   491.4 2501.54
   506.4 2502.01   539.1 2502.87     569 2511.24   683.5 2554.81   693.5 2560.48
   713.3 2569.42   748.1 2591.44   772.9 2597.51   812.6 2615.12   842.4  2626.1
   857.3 2628.69   911.9 2631.71   951.6 2640.42  1021.1  2657.9  1060.8 2664.04
#Mann= 3 , 0 , 0
       0      .1       0   491.4    .045       0   506.4      .1       0
Bank Sta=491.4,506.4
XS Rating Curve= 0 ,0
Exp/Cntr=0.3,0.1

Type RM Length L Ch R = 1 ,24396.4 ,235.7,239.7,258.3
XS GIS Cut Line= 4
     1888065.084      182620.615     1887848.323      182976.431
     1887701.089      183213.642     1887619.292      183565.368
#Sta/Elev= 30
       0 2609.91    14.9 2605.95   104.2 2589.38   148.8 2574.79   173.6 2563.23
   208.3 2550.51     253 2541.49   272.8 2535.98   307.5 2533.98   352.2 2517.14
     367 2513.87   386.9 2510.28   461.5 2502.23   501.4 2502.04     529 2500.12
   531.3 2499.98     544 2501.53   561.2 2507.07   596.1 2523.49     651  2556.9
   690.8 2573.54   715.6 2579.79   755.2 2585.18     775 2590.14   819.5 2596.94
   844.2 2604.67   888.8 2623.58     963 2646.79  1022.3 2662.64  1056.9    2669
#Mann= 3 , 0 , 0
       0      .1       0     529    .045       0     544      .1       0
Bank Sta=529,544
XS Rating Curve= 0 ,0
Exp/Cntr=0.3,0.1

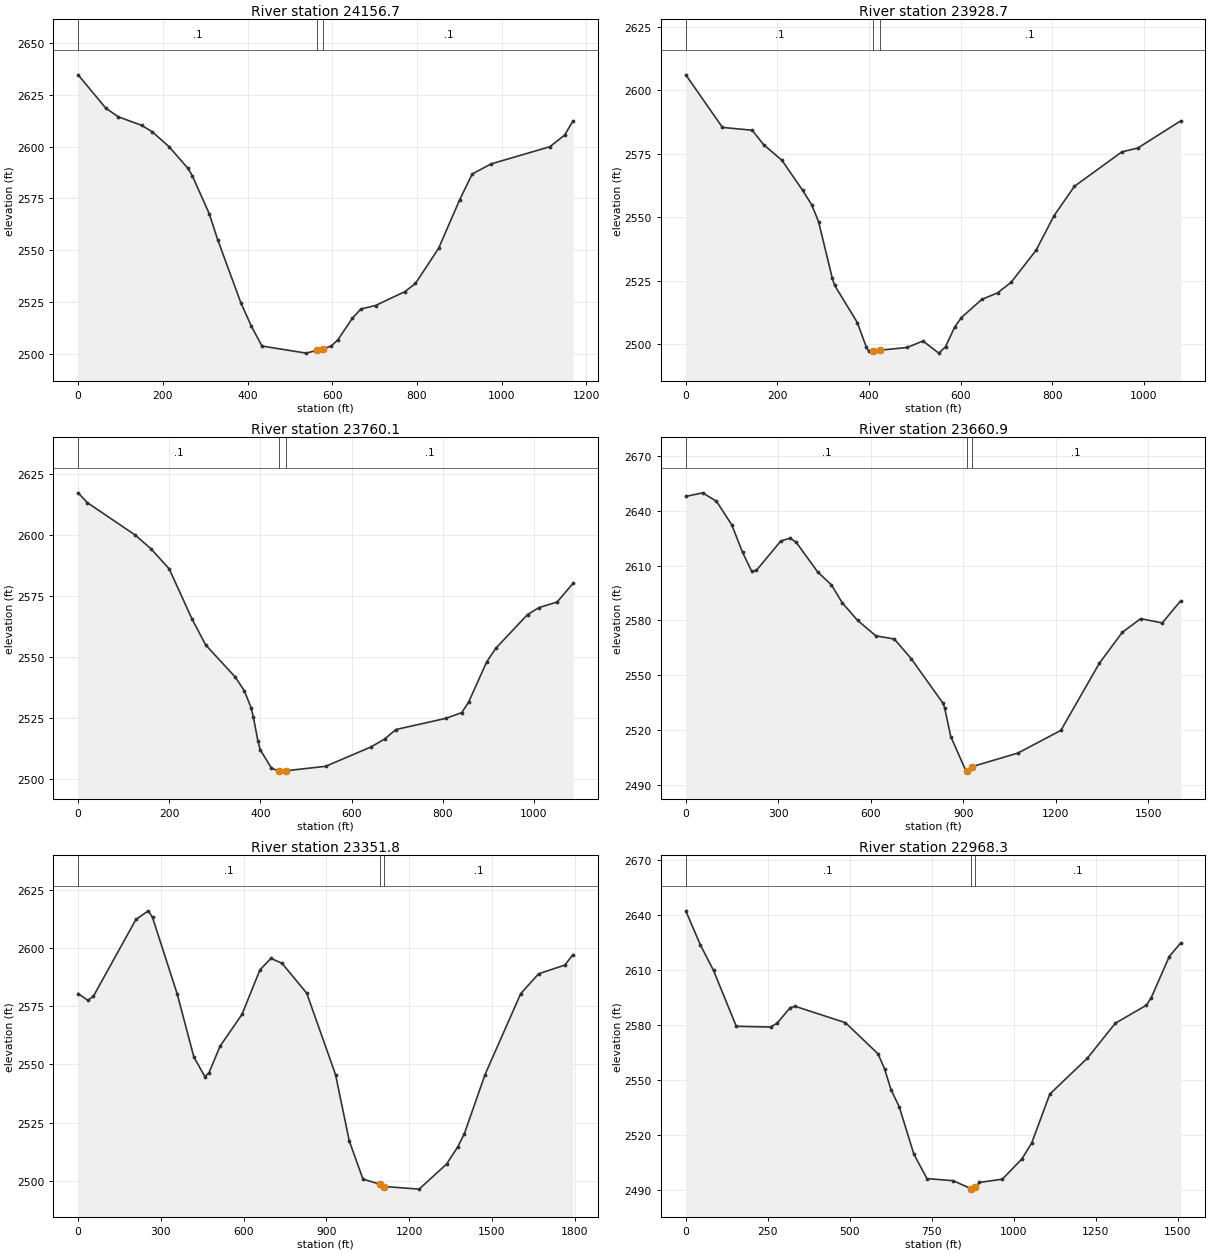
Type RM Length L Ch R = 1 ,24156.7 ,225.5,228,230.4
XS GIS Cut Line= 4
     1887905.581      182518.369      1887668.37      182857.826
     1887475.997      183098.189     1887357.542      183528.559
#Sta/Elev= 30
       0 2634.68    64.9 2618.66    94.8  2614.4   149.7 2610.29   174.6 2607.24
   214.6 2599.98   259.4 2589.46   269.4 2585.96   309.4 2567.64   329.3 2555.13
   384.2 2524.54   409.1 2513.18     434 2503.68   538.3 2500.26   564.2  2501.6
   579.2 2502.34   597.8 2503.75   612.8  2506.6   647.5 2517.14   667.4 2521.56
   702.1 2523.26   771.6 2529.99   796.4 2533.93   850.9 2550.83   900.5  2574.2
   930.3 2586.78   974.9 2591.65  1113.8 2599.96  1148.5 2605.57  1168.4 2612.43
#Mann= 3 , 0 , 0
       0      .1       0   564.2    .045       0   579.2      .1       0
Bank Sta=564.2,579.2
XS Rating Curve= 0 ,0
Exp/Cntr=0.3,0.1

Type RM Length L Ch R = 1 ,23928.7 ,173.3,168.6,164.9
XS GIS Cut Line= 4
     1887791.065      182469.291     1887557.944       182743.31
     1887296.195      182976.431     1887210.308      183336.337
#Sta/Elev= 30
       0 2606.05      80 2585.35   144.9 2584.24   169.9 2578.56   209.9 2572.41
   254.8 2560.64   274.8 2554.91   289.8 2548.25   319.8 2525.98   324.8 2523.21
   374.6 2508.48   394.3 2498.74   399.3 2497.26   408.5 2497.23   423.5 2497.64
   483.2 2498.71   517.7 2501.27   552.3 2496.49   567.1 2499.03   586.9 2506.74
   601.7  2510.5   646.1 2517.64   680.7 2520.22   710.3  2524.4   764.6 2536.98
     804 2550.64   848.4 2562.17     952 2575.73   986.6 2577.22  1080.3 2587.91
#Mann= 3 , 0 , 0
       0      .1       0   408.5    .045       0   423.5      .1       0
Bank Sta=408.5,423.5
XS Rating Curve= 0 ,0
Exp/Cntr=0.3,0.1

Type RM Length L Ch R = 1 ,23760.1 ,100.9,99.2,97.1
XS GIS Cut Line= 4
     1887713.358      182403.853     1887451.609      182596.076
     1887243.027      182886.454      1887169.41      183283.169
#Sta/Elev= 30
       0  2617.2      20  2613.2   124.9 2599.96   159.9 2594.28   199.8 2586.08
   249.8 2565.58   279.8 2554.97   344.6 2541.84   364.5 2536.25   379.4  2529.3
   384.3 2525.56   394.3 2515.79   399.2 2512.18   424.1 2504.58   440.6 2503.36
   443.9 2503.34   455.6 2503.48   543.2 2505.32   642.6 2513.24   672.4 2516.46
   697.2 2520.36   806.8 2524.93   841.7 2527.29   856.6 2531.55   896.5 2548.08
   916.4 2553.62   986.1 2567.42    1011 2570.24  1050.9 2572.53  1085.8 2580.17
#Mann= 3 , 0 , 0
       0      .1       0   440.6    .045       0   455.6      .1       0
Bank Sta=440.6,455.6
XS Rating Curve= 0 ,0
Exp/Cntr=0.3,0.1

Type RM Length L Ch R = 1 ,23660.9 ,330.9,309.1,286.3
XS GIS Cut Line= 4
     1888028.276       182232.08     1887439.339      182416.123
      1887165.32      182870.095     1887119.447      183326.335
#Sta/Elev= 30
       0 2647.73    54.7 2649.69    99.5 2645.08   149.3 2632.18   184.1 2617.18
     214  2606.8   228.9 2607.33   308.5 2623.42   338.4 2624.93   358.3 2622.69
   427.9 2606.49   472.7  2599.4   507.6 2589.66   557.3 2580.05     617 2571.56
   676.5 2569.88     731 2559.22   835.1 2534.69     840 2532.22   859.8 2516.56
   909.4 2497.72   912.3 2497.76   927.3 2500.09  1077.9  2507.6  1217.1 2519.97
  1341.7 2556.58  1416.4 2573.53  1476.2 2580.98    1546 2578.64  1605.8 2590.73
#Mann= 3 , 0 , 0
       0      .1       0   912.3    .045       0   927.3      .1       0
Bank Sta=912.3,927.3
XS Rating Curve= 0 ,0
Exp/Cntr=0.3,0.1

Type RM Length L Ch R = 1 ,23351.8 ,383.8,383.4,376.5
XS GIS Cut Line= 4
      1887352.17      181643.543     1886894.108      182375.624
      1887086.33      182833.687     1887074.061      183267.209
#Sta/Elev= 30
       0 2580.53    34.9 2577.61    54.9  2579.3   209.6 2612.47   254.6 2616.15
   269.6 2613.28   359.4 2580.22   419.3 2553.26   459.2 2544.78   474.2 2546.38
   514.2 2557.82     594 2571.57   658.9 2590.72   698.8 2595.66   738.8  2593.6
   828.6 2580.68   933.1 2545.62   982.8 2517.09  1032.5  2500.6  1094.9 2498.39
  1109.9 2497.44  1236.2 2496.31  1335.5  2507.1  1375.3 2514.34  1400.2 2520.22
    1475 2545.65  1604.6 2580.53  1669.4 2589.05  1764.1 2592.78    1794 2597.31
#Mann= 3 , 0 , 0
       0      .1       0  1094.9    .045       0  1109.9      .1       0
Bank Sta=1094.9,1109.9
XS Rating Curve= 0 ,0
Exp/Cntr=0.3,0.1

Type RM Length L Ch R = 1 ,22968.3 ,424.6,421.7,421.8
XS GIS Cut Line= 4
     1886085.602       182232.08      1886637.73      182604.256
     1886919.929      182947.802     1886997.842      183339.312
#Sta/Elev= 30
       0  2642.4    44.7 2623.72    84.5 2609.89     154 2579.42   258.4 2579.01
   278.3 2581.06     318  2589.5   332.9 2590.36     487 2581.38   586.4  2564.4
   606.2 2556.24   626.1  2544.8     651 2535.54   695.8 2509.63   735.8 2496.33
   815.7  2495.2   868.7 2490.93   875.7  2490.6   883.7 2491.87   895.6 2494.23
   965.6 2496.04  1025.5 2507.11  1055.5  2515.9  1110.4 2542.45  1225.2 2562.04
    1310 2581.06  1404.8  2590.9  1419.8    2595  1474.7 2617.45  1509.6 2624.88
#Mann= 3 , 0 , 0
       0      .1       0   868.7    .045       0   883.7      .1       0
Bank Sta=868.7,883.7
XS Rating Curve= 0 ,0
Exp/Cntr=0.3,0.1

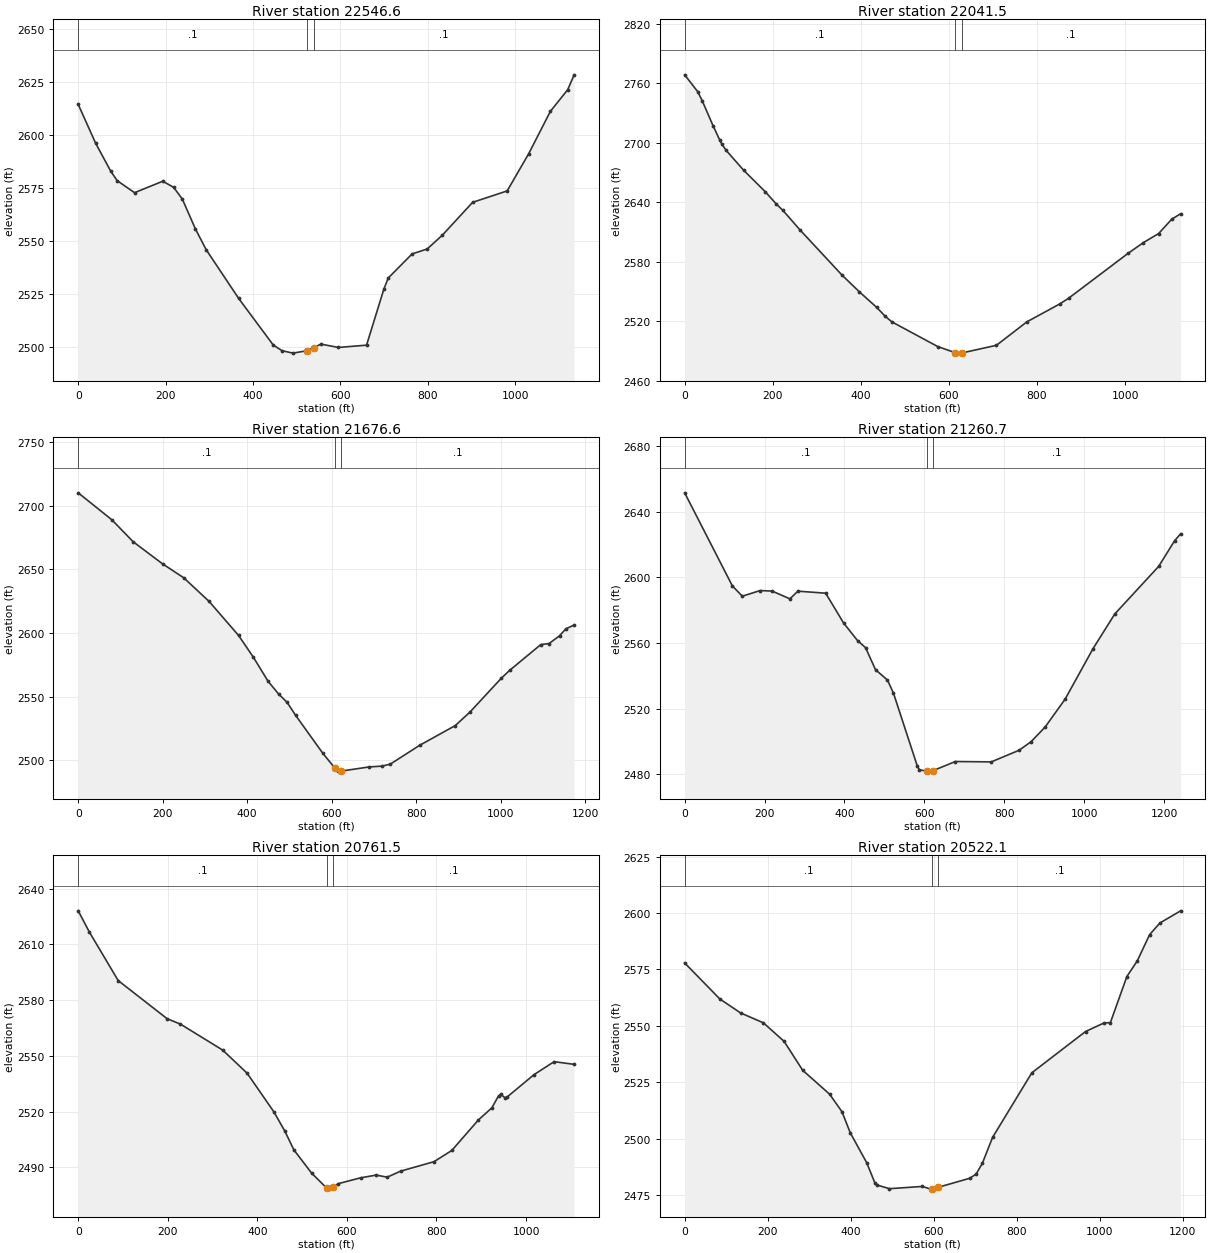
Type RM Length L Ch R = 1 ,22546.6 ,511.4,505.1,498.9
XS GIS Cut Line= 4
     1886218.487      182484.097      1886400.52      182808.748
     1886613.192      183201.372     1886690.215      183508.312
#Sta/Elev= 30
       0 2614.36    39.7 2596.15    74.4 2582.91    89.3 2578.43     129 2572.78
   193.5 2578.17   218.4 2575.31   238.2 2569.82     268 2555.83   292.8 2545.97
   367.2 2523.02   446.6 2501.01   466.5  2498.4   491.3 2497.24   523.8 2498.37
   538.8 2499.85   555.8 2501.48   595.5 2499.91     660 2500.99   699.6 2527.34
   709.6 2532.59   764.2 2543.94   798.9 2546.29   833.6 2552.79   902.8 2568.24
   981.9 2573.62  1031.3 2591.18  1080.8 2611.08  1120.4 2621.26  1135.2 2628.27
#Mann= 3 , 0 , 0
       0      .1       0   523.8    .045       0   538.8      .1       0
Bank Sta=523.8,538.8
XS Rating Curve= 0 ,0
Exp/Cntr=0.3,0.1

Type RM Length L Ch R = 1 ,22041.5 ,365.1,364.8,364.6
XS GIS Cut Line= 4
     1885799.314      182816.927     1885966.997      183131.845
      1886263.19      183436.795     1886503.191      183683.376
#Sta/Elev= 30
       0 2768.47    29.7 2751.43    39.6 2742.57    64.4 2717.19    79.3 2703.02
    84.2 2698.74    94.2 2692.26   133.8 2672.33   183.3 2650.46   208.1 2638.21
     223 2631.82   262.6 2611.74   356.8 2566.77   396.3 2549.84   435.9 2534.05
   455.6  2524.9   470.5 2519.42   574.3 2494.58     614  2488.4   623.7 2487.91
     629 2488.06   707.8  2495.8     777 2519.47   851.7 2537.52   871.7 2543.25
  1006.3 2588.38  1041.2 2599.24  1076.1 2608.48    1106    2623    1126 2628.39
#Mann= 3 , 0 , 0
       0      .1       0     614    .045       0     629      .1       0
Bank Sta=614,629
XS Rating Curve= 0 ,0
Exp/Cntr=0.3,0.1

Type RM Length L Ch R = 1 ,21676.6 ,420.1,416,411.8
XS GIS Cut Line= 4
     1885488.486      183090.947     1885782.954      183463.122
     1885999.716      183683.973     1886339.172      183876.196
#Sta/Elev= 30
       0 2710.07    79.9 2688.82   129.9 2671.71   199.8 2654.26   249.8 2643.36
   309.7 2624.85   379.7 2598.06   414.6    2581   449.6 2562.03   474.6 2552.02
   494.5 2545.54   514.5 2535.43   579.4 2505.39   607.9 2493.82   614.3 2491.89
   619.3 2491.52   622.9 2491.56   689.2 2494.84   719.2 2495.44   739.1 2497.08
   808.7 2511.87   892.7  2527.3   927.2 2537.81  1001.3 2564.35  1021.1 2570.58
  1095.1 2590.89  1114.9 2591.73  1139.6 2597.84  1154.4 2603.25  1174.1 2606.25
#Mann= 3 , 0 , 0
       0      .1       0   607.9    .045       0   622.9      .1       0
Bank Sta=607.9,622.9
XS Rating Curve= 0 ,0
Exp/Cntr=0.3,0.1

Type RM Length L Ch R = 1 ,21260.7 ,491.5,499.2,506.9
XS GIS Cut Line= 4
     1885210.596      183483.825     1885460.076      183774.204
     1885845.783      184042.366     1886208.517      184183.188
#Sta/Elev= 30
       0 2651.68   119.3 2594.92   144.2 2588.58   188.9 2592.02   218.8 2591.72
   263.5 2586.98   283.4 2591.66     353 2590.42   397.8 2572.27   432.8 2561.49
   452.8  2557.2   477.8 2543.73   507.8 2537.38   522.8 2529.36   582.7 2484.73
   587.7 2482.62   606.1 2481.82   607.7 2481.81   621.1 2482.03   677.7 2487.68
   767.6 2487.45   837.6 2494.57   867.6 2499.84   902.5 2508.74   952.4  2525.7
  1022.2 2556.49  1077.1 2577.81  1186.8  2606.8  1226.7 2622.44  1241.7  2626.7
#Mann= 3 , 0 , 0
       0      .1       0   606.1    .045       0   621.1      .1       0
Bank Sta=606.1,621.1
XS Rating Curve= 0 ,0
Exp/Cntr=0.3,0.1

Type RM Length L Ch R = 1 ,20761.5 ,239.5,239.4,240.1
XS GIS Cut Line= 4
     1885024.679      183835.941     1885286.429      184191.757
     1885450.023      184428.967     1885740.401      184670.268
#Sta/Elev= 30
       0 2628.01    24.8 2616.64    89.3 2590.49   198.5 2569.99   228.3 2567.07
   322.6  2553.1   377.2 2540.66   436.8 2519.92   461.6 2509.42   481.5 2499.45
   521.2 2486.92   554.6 2478.91     561 2478.31   569.6  2479.5   580.8 2481.26
   630.5 2484.39   665.3 2485.86   690.1 2484.75   719.9 2487.98   794.5 2493.08
   834.2 2499.11   893.8 2515.58   923.6 2522.02   938.5 2528.47   943.5 2529.26
   953.4 2527.37   958.4    2528    1018 2539.93  1062.7 2546.88  1107.4 2545.42
#Mann= 3 , 0 , 0
       0      .1       0   554.6    .045       0   569.6      .1       0
Bank Sta=554.6,569.6
XS Rating Curve= 0 ,0
Exp/Cntr=0.3,0.1

Type RM Length L Ch R = 1 ,20522.1 ,349.9,347.5,345
XS GIS Cut Line= 4
     1884847.017      184034.621      1885116.31       184264.73
     1885338.762       184629.98     1885688.888      184849.577
#Sta/Elev= 30
       0 2577.83    84.8 2561.85   134.7 2555.68   189.6  2551.3   239.5 2543.11
   284.4 2530.25   349.2 2519.68   379.1 2511.88     399 2502.58   438.8 2489.24
   458.6 2480.25   463.6 2479.39   493.4 2477.78     573 2478.77   592.9 2477.58
   596.4 2477.63   611.4 2478.41   687.4 2482.42   702.3 2484.26   717.2 2488.94
   742.1 2500.53   836.6 2529.14   966.1 2547.44  1010.9 2551.26  1025.9 2551.36
  1065.7 2571.82  1090.6  2578.7  1120.5 2590.38  1145.4 2595.56  1195.2 2600.93
#Mann= 3 , 0 , 0
       0      .1       0   596.4    .045       0   611.4      .1       0
Bank Sta=596.4,611.4
XS Rating Curve= 0 ,0
Exp/Cntr=0.3,0.1

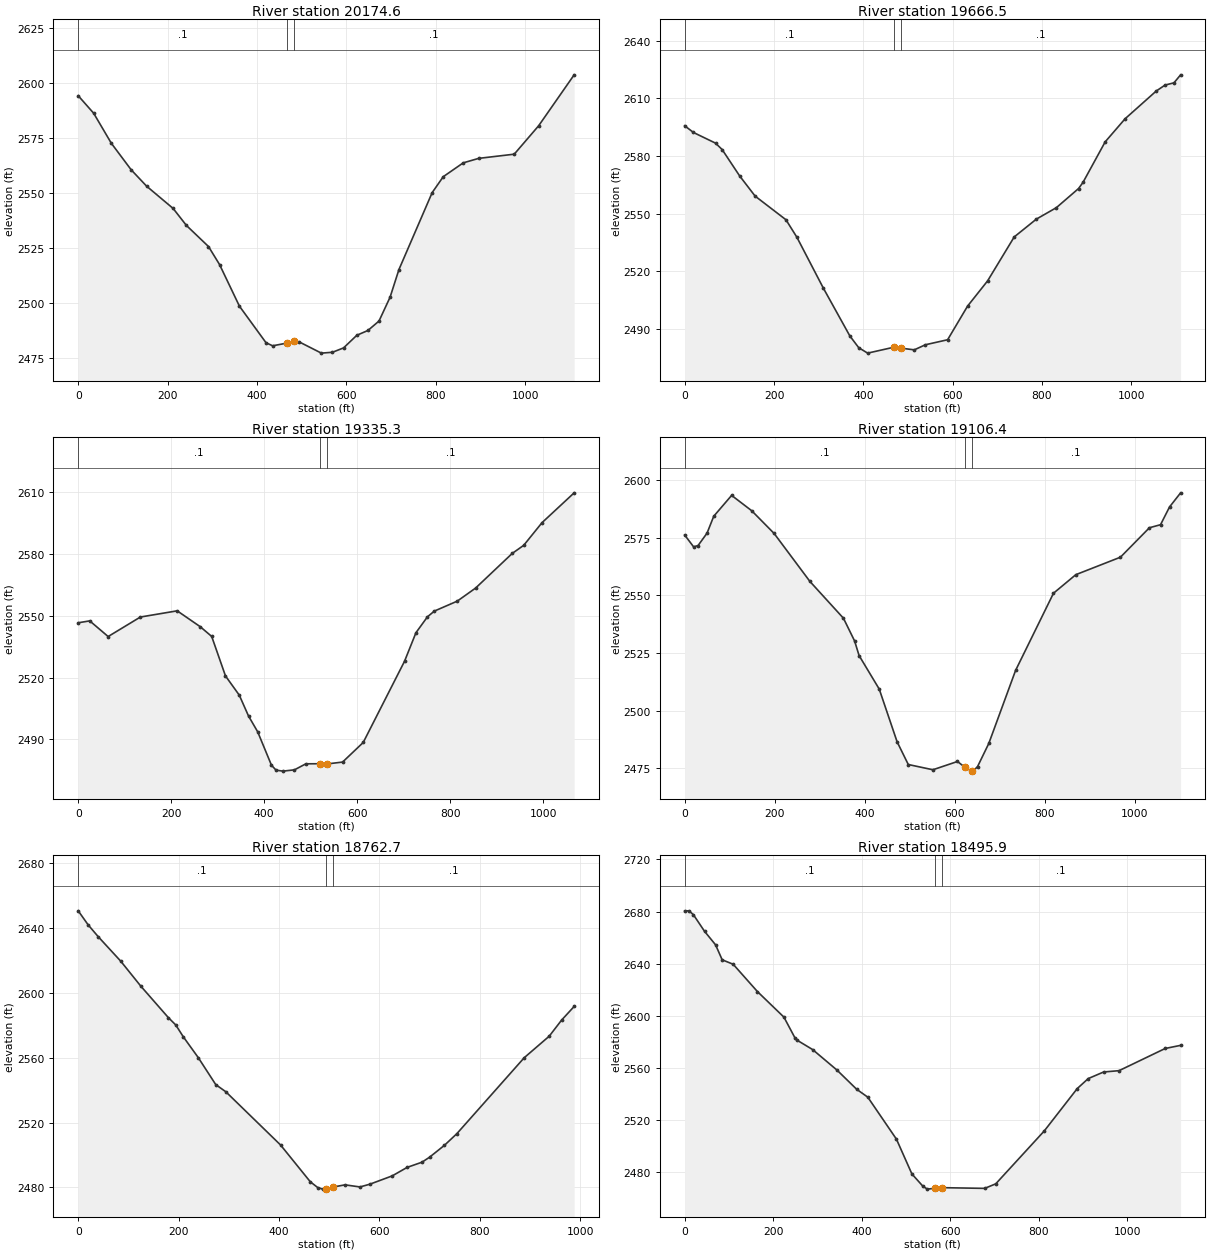
Type RM Length L Ch R = 1 ,20174.6 ,520.1,508.1,498.9
XS GIS Cut Line= 4
     1884641.148      184276.983     1884907.393      184512.763
     1885172.974      184846.058     1885377.346       185101.93
#Sta/Elev= 30
       0  2594.3    34.6 2586.34    74.1  2572.7   118.6 2560.62   153.1  2553.2
   212.4 2543.08     242 2535.39   291.4 2525.81   316.1 2517.64   360.6 2498.72
   420.1 2482.11   434.9 2480.72   467.5 2481.97   482.5 2482.68   494.4 2482.48
   543.9 2477.39   568.7 2477.78   593.5 2479.76   623.2  2485.5     648 2487.68
   672.8 2491.96   697.6 2502.81   717.4 2515.36   791.7 2550.29   816.5 2557.52
   861.2 2563.81   895.9 2565.85   975.3 2567.75  1029.9 2580.66  1109.3 2603.79
#Mann= 3 , 0 , 0
       0      .1       0   467.5    .045       0   482.5      .1       0
Bank Sta=467.5,482.5
XS Rating Curve= 0 ,0
Exp/Cntr=0.3,0.1

Type RM Length L Ch R = 1 ,19666.5 ,332.4,331.2,330
XS GIS Cut Line= 4
     1884268.531      184841.388     1884592.811      184943.644
     1884954.603      185152.149     1885275.812      185297.529
#Sta/Elev= 30
       0 2595.76    19.7 2592.25      69 2586.71    83.8 2583.39   123.2 2569.58
   157.7 2559.12   226.7 2546.81   251.3 2537.66   310.4 2511.21   369.8 2486.28
   389.7 2480.16   409.6 2477.35   469.1 2480.47   484.1 2479.94     514 2479.06
   538.9 2481.71   588.6 2484.32   633.3 2501.84   678.1 2514.97   737.7 2537.86
   787.4 2547.16   832.1 2553.11   881.7 2563.06   891.7 2566.28   941.3 2587.37
     986 2599.42  1055.6 2613.84  1075.4 2616.95  1095.3 2618.11  1110.2 2622.28
#Mann= 3 , 0 , 0
       0      .1       0   469.1    .045       0   484.1      .1       0
Bank Sta=469.1,484.1
XS Rating Curve= 0 ,0
Exp/Cntr=0.3,0.1

Type RM Length L Ch R = 1 ,19335.3 ,225.7,228.9,232
XS GIS Cut Line= 4
     1884151.108      185082.698     1884490.565      185266.741
     1884817.752      185377.167     1885144.939      185450.784
#Sta/Elev= 30
       0 2546.62    24.8 2547.54    64.4 2539.94   133.7 2549.41   212.9 2552.42
   262.4 2544.73   287.1    2540   316.8 2520.81   346.5 2511.47   366.3 2501.38
   386.1 2493.67   415.7 2477.47   425.6 2475.07   440.4  2474.6   465.1 2475.22
   489.7 2478.15   519.2 2478.19   534.2 2478.06   568.7    2479   613.1 2488.52
   701.9 2527.92   726.5  2541.8   751.2  2549.5     766 2552.29   815.3 2557.12
   854.8 2563.47   933.7 2580.31   958.3 2584.22   997.8 2595.25  1066.8 2609.71
#Mann= 3 , 0 , 0
       0      .1       0   519.2    .045       0   534.2      .1       0
Bank Sta=519.2,534.2
XS Rating Curve= 0 ,0
Exp/Cntr=0.3,0.1

Type RM Length L Ch R = 1 ,19106.4 ,348,343.7,339.1
XS GIS Cut Line= 3
     1884099.269      185176.854     1884686.679       185576.25
     1885051.457      185718.108
#Sta/Elev= 30
       0 2576.13    19.9 2570.98    29.8 2571.57    49.7 2576.95    64.6 2584.27
   104.3 2593.31     149 2586.64   198.7  2576.8   278.2    2556   352.7 2540.04
   377.5 2530.17   387.4 2523.87   432.2 2509.32   471.9 2486.46   496.7 2476.62
   551.4 2474.34     606 2477.93   622.2 2475.47   637.2 2473.76   640.8 2473.75
   650.7 2475.75   675.6 2485.76   735.1 2517.42   819.3 2550.89   868.9 2558.93
     968 2566.51  1032.4 2579.28  1057.1  2580.6    1077 2588.27  1101.7 2594.42
#Mann= 3 , 0 , 0
       0      .1       0   622.2    .045       0   637.2      .1       0
Bank Sta=622.2,637.2
XS Rating Curve= 0 ,0
Exp/Cntr=0.3,0.1

Type RM Length L Ch R = 1 ,18762.7 ,271.1,266.8,262.4
XS GIS Cut Line= 4
     1883962.976      185508.042     1884249.264      185659.366
      1884609.17      185835.229     1884821.842      185990.643
#Sta/Elev= 30
       0 2650.62    19.9 2641.92    39.8 2634.69    84.7 2619.57   124.6  2604.2
   179.4 2584.81   194.3 2580.23   209.2 2572.97   239.1  2560.1     274 2543.42
   293.9 2539.06     403 2506.21   462.3  2483.5   477.1 2479.94     487 2478.98
   493.1  2479.2   508.1  2480.3   531.5 2481.62   561.2 2480.32     581 2482.03
   625.5 2487.16   655.2  2492.4   684.8  2495.6   699.7 2498.65   729.4 2505.99
   754.2 2513.19   888.4 2560.04   938.1 2573.29     963  2583.3   987.8 2591.64
#Mann= 3 , 0 , 0
       0      .1       0   493.1    .045       0   508.1      .1       0
Bank Sta=493.1,508.1
XS Rating Curve= 0 ,0
Exp/Cntr=0.3,0.1

Type RM Length L Ch R = 1 ,18495.9 ,164.4,169.9,175.4
XS GIS Cut Line= 4
     1883817.734      185758.619     1884163.378       185936.28
     1884539.643      186034.436      1884836.29      186206.298
#Sta/Elev= 30
       0 2680.55      10 2680.53    19.9 2677.49    44.8 2664.85    69.8 2654.42
    84.7 2642.93   109.6  2639.5   164.4  2618.5   224.2 2598.88   249.1 2582.96
   254.1 2581.13     289 2573.98   343.8 2558.28   388.6 2543.45   413.6 2537.41
   478.4 2505.13   513.3 2478.42   538.2 2468.95   548.2 2466.76   565.3 2467.41
   580.3 2467.89   677.8 2467.34   702.7 2470.83   812.3 2511.46   886.8 2544.02
   911.6 2551.68   946.4 2556.75   981.2 2557.76  1085.5 2574.81  1120.3 2577.21
#Mann= 3 , 0 , 0
       0      .1       0   565.3    .045       0   580.3      .1       0
Bank Sta=565.3,580.3
XS Rating Curve= 0 ,0
Exp/Cntr=0.3,0.1

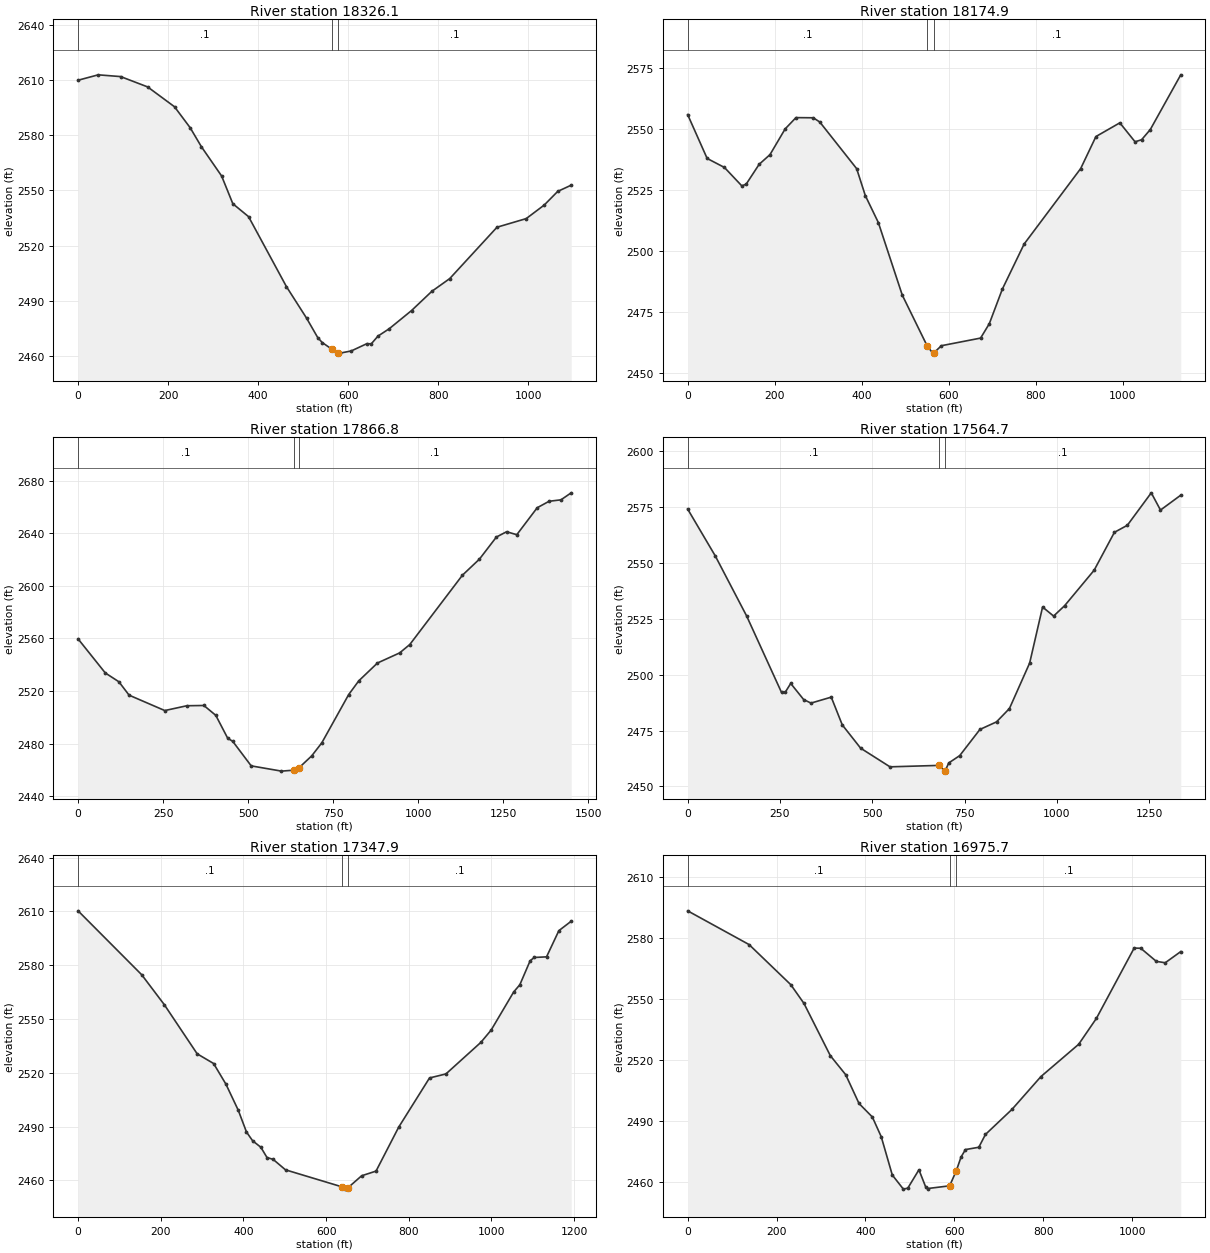
Type RM Length L Ch R = 1 ,18326.1 ,156.4,151.2,146
XS GIS Cut Line= 4
     1883721.749      185968.974     1884093.483      186040.157
     1884397.988      186206.251     1884765.766      186241.842
#Sta/Elev= 30
       0  2609.8    44.8 2612.73    94.6 2611.77   154.4 2606.18   214.1 2595.41
     249 2583.99   273.9 2573.69   318.7 2557.86   343.6  2542.8   378.5  2535.8
   462.7  2497.8   507.3 2480.74   532.1 2470.19     542 2467.52   562.8    2464
   577.8 2461.96   581.6 2461.76   606.4 2462.93   641.1 2466.88     651 2466.81
   665.9 2471.01   690.7 2474.97   740.3 2484.84   785.3 2495.26   825.2  2502.2
   930.1 2530.06     995 2534.74  1034.9 2542.08  1064.9 2549.49  1094.8 2552.87
#Mann= 3 , 0 , 0
       0      .1       0   562.8    .045       0   577.8      .1       0
Bank Sta=562.8,577.8
XS Rating Curve= 0 ,0
Exp/Cntr=0.3,0.1

Type RM Length L Ch R = 1 ,18174.9 ,307.2,308,305.8
XS GIS Cut Line= 4
     1883636.663      186212.752     1884044.772      186219.674
     1884425.127      186326.009     1884746.127      186402.075
#Sta/Elev= 30
       0 2555.74    44.8 2537.78    84.6 2534.08   124.4 2526.56   134.4 2527.23
   164.3 2535.38   189.2 2539.34     224 2549.87   248.9  2554.5   288.7 2554.43
   303.6  2552.7   388.3 2533.61   408.2 2522.58   438.2 2511.51   493.2 2481.79
   550.2 2461.06   563.1 2458.06   565.2  2458.1   583.1  2461.1   673.1 2464.22
   693.1  2470.1   723.1 2484.29   773.1 2502.73   903.1 2533.65   938.1 2546.75
     993 2552.36    1028  2544.6    1043 2545.44    1063 2549.61    1133 2572.02
#Mann= 3 , 0 , 0
       0      .1       0   550.2    .045       0   565.2      .1       0
Bank Sta=550.2,565.2
XS Rating Curve= 0 ,0
Exp/Cntr=0.3,0.1

Type RM Length L Ch R = 1 ,17866.8 ,303.3,302.1,320.5
XS GIS Cut Line= 4
     1883631.699      186240.123     1884005.086      186472.669
     1884365.116      186595.564     1884993.615      186628.658
#Sta/Elev= 30
       0 2559.67      80 2533.79     120 2527.08     150 2516.91   254.9 2505.21
   319.9 2508.87   369.9 2509.06   404.9 2501.57   439.9 2484.19   454.7 2481.82
     509 2463.18     598 2459.19   634.6 2459.92   649.6 2461.74   686.9 2470.79
   716.6 2480.71   795.6 2517.37   825.3 2527.81   880.2 2541.34   945.2 2548.99
   975.2 2555.37    1130 2608.07    1180 2620.27  1229.9 2637.07  1259.9 2641.08
  1289.8 2638.82  1349.8  2659.3  1384.7 2664.22  1419.7 2665.32  1449.7 2670.64
#Mann= 3 , 0 , 0
       0      .1       0   634.6    .045       0   649.6      .1       0
Bank Sta=634.6,649.6
XS Rating Curve= 0 ,0
Exp/Cntr=0.3,0.1

Type RM Length L Ch R = 1 ,17564.7 ,202.8,216.8,223.1
XS GIS Cut Line= 4
     1883592.378      186284.636     1883930.657      186486.517
     1884093.362      186860.394     1884398.076      187298.916
#Sta/Elev= 30
       0 2574.02    74.8 2553.08   159.6 2526.28   254.3 2492.04   264.3 2492.13
   279.2 2496.06   314.2 2488.87   334.1 2487.28     389 2489.94   418.8 2477.55
   468.5 2467.14   548.1 2458.79   681.1 2459.43   696.1 2456.95   697.3 2456.87
   707.2 2460.53     737 2463.81   791.7  2475.5   836.6 2478.88   871.6 2484.84
   926.4 2505.18   961.4 2530.22   991.3 2526.18  1021.3 2530.85  1101.1 2546.68
    1156 2563.62    1191 2566.76  1255.8 2581.27  1280.8 2573.56  1335.7 2580.22
#Mann= 3 , 0 , 0
       0      .1       0   681.1    .045       0   696.1      .1       0
Bank Sta=681.1,696.1
XS Rating Curve= 0 ,0
Exp/Cntr=0.3,0.1

Type RM Length L Ch R = 1 ,17347.9 ,380.1,372.2,365.7
XS GIS Cut Line= 4
     1883439.476      186346.459      1883852.55      186604.118
     1883942.526      186914.946      1884102.03      187262.583
#Sta/Elev= 30
       0 2610.33     154 2574.67   208.6 2558.01   288.1  2530.6   327.9 2525.19
   357.7 2513.67   387.5 2499.16   407.4    2487   422.3  2482.1   442.1 2478.51
     457 2472.78   471.9 2471.74   501.8 2465.91   638.3 2456.43   646.2 2455.15
   653.3    2456     686  2462.6   720.8  2465.2   775.6  2489.7   850.2 2517.14
   889.9 2519.38   974.4 2536.98   999.2 2543.81  1053.8 2565.09  1068.7 2569.12
  1093.6 2582.49  1103.5 2584.32  1133.3 2584.67  1163.1 2599.27  1192.9 2604.53
#Mann= 3 , 0 , 0
       0      .1       0   638.3    .045       0   653.3      .1       0
Bank Sta=638.3,653.3
XS Rating Curve= 0 ,0
Exp/Cntr=0.3,0.1

Type RM Length L Ch R = 1 ,16975.7 ,206.1,211.6,217.1
XS GIS Cut Line= 4
     1883375.905      186433.608     1883504.914      186759.532
     1883705.316      187127.618     1883905.718      187401.637
#Sta/Elev= 30
       0 2593.53   138.2 2576.91     232 2557.16   261.7 2547.91   320.9 2522.21
   355.5 2512.83   385.4 2498.67   415.4    2492   435.4  2482.3   460.3 2463.43
   485.2 2456.48   495.2 2456.97   520.2    2466   535.1 2457.72   540.1 2456.78
   589.3 2458.11   604.3 2465.55     615 2472.32   624.9 2475.96   654.9  2477.1
   669.8  2483.4   729.7  2495.8   794.6 2511.91   879.5 2527.81   919.4 2540.58
  1004.3  2575.2  1019.2 2575.09  1054.2 2568.63  1074.2 2567.96  1109.1 2573.46
#Mann= 3 , 0 , 0
       0      .1       0   589.3    .045       0   604.3      .1       0
Bank Sta=589.3,604.3
XS Rating Curve= 0 ,0
Exp/Cntr=0.3,0.1