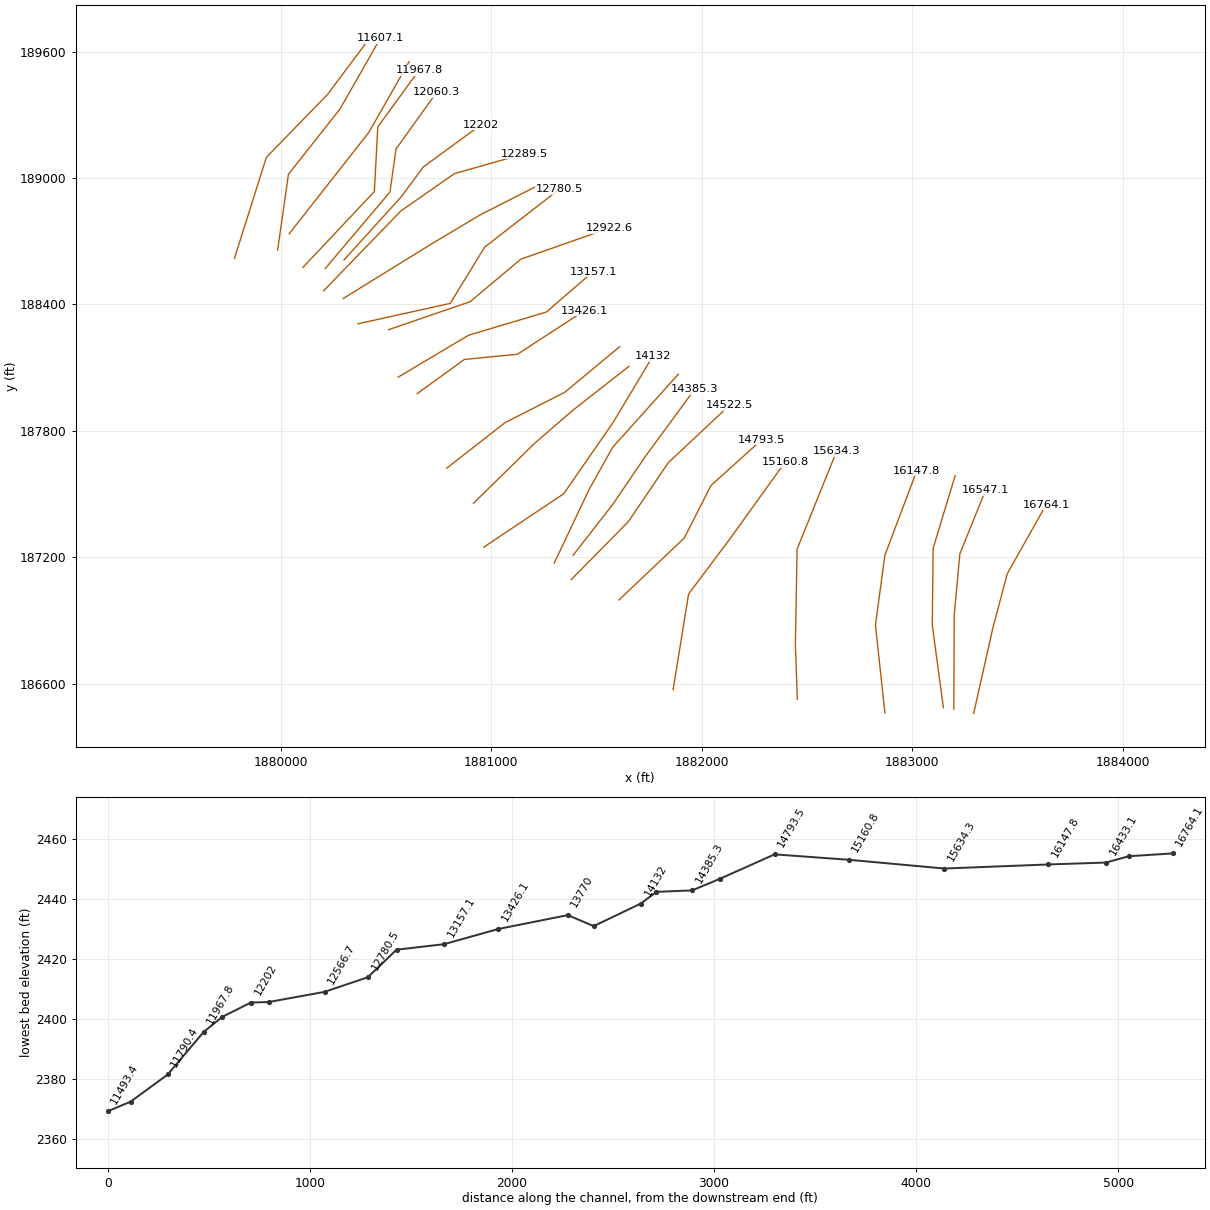
HEC-RAS study MilamFk2.prj: MilamFk2

--- MilamFk2.g01 (geometry) --- (continued)

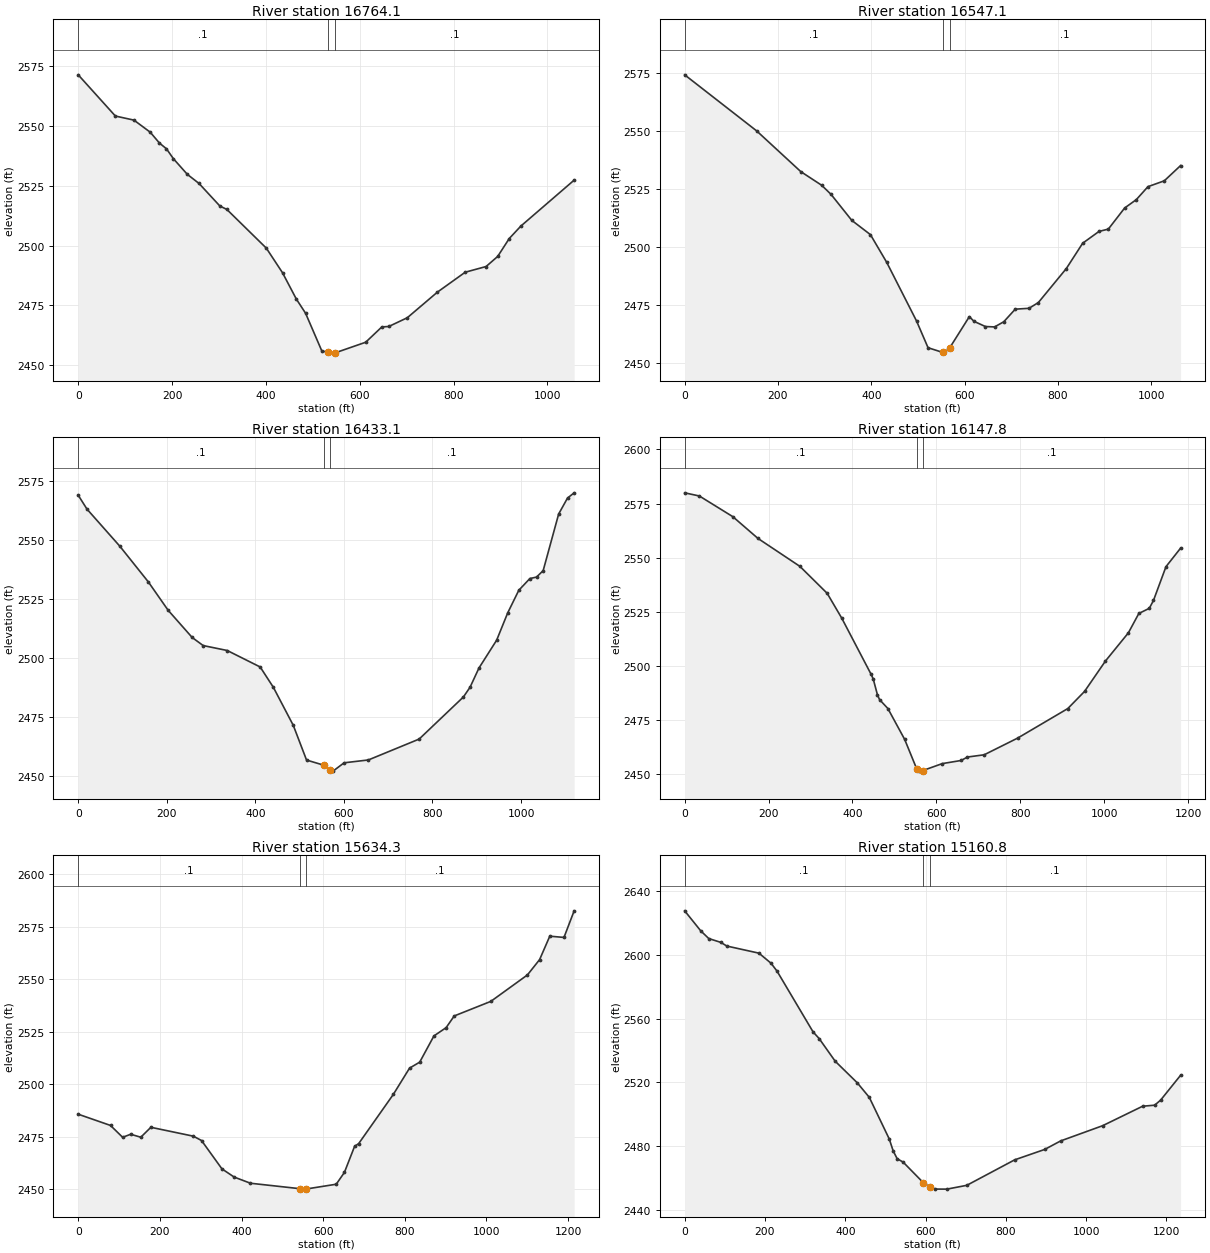
Type RM Length L Ch R = 1 ,16764.1 ,213,217,221.1
XS GIS Cut Line= 4
     1883292.729      186458.836     1883382.705       186859.64
     1883452.232       187121.39     1883636.275      187448.577
#Sta/Elev= 30
       0 2571.38    79.2 2554.16   118.8 2552.45   153.4 2547.42   173.2 2542.85
   188.1 2540.47   202.9 2536.32   232.6 2529.78   257.4    2526   301.9 2516.56
   316.8 2515.13   400.9 2498.96   435.4 2488.68   464.9 2477.67   484.6 2471.74
   519.1 2456.03   531.8 2455.42   543.7 2455.08   546.8 2455.14   612.7 2459.63
   647.1 2466.03   661.9 2466.21   701.4 2469.87   765.6 2480.58   824.8 2488.89
   869.3 2491.27     894 2495.48   918.7 2502.98   943.4 2508.17    1057 2527.38
#Mann= 3 , 0 , 0
       0      .1       0   531.8    .045       0   546.8      .1       0
Bank Sta=531.8,546.8
XS Rating Curve= 0 ,0
Exp/Cntr=0.3,0.1

Type RM Length L Ch R = 1 ,16547.1 ,112.1,114,115.8
XS GIS Cut Line= 4
     1883198.265      186479.647     1883200.329      186927.459
     1883227.156       187216.37     1883348.911      187517.663
#Sta/Elev= 30
       0 2574.17   154.2    2550   248.8 2532.44   293.6 2526.54   313.5 2522.66
   358.2 2511.39   398.1 2505.25   432.9 2493.34     497 2467.98   521.6 2456.48
   553.2 2454.45     556 2454.15   568.2 2456.49   610.1 2469.89   619.9 2467.88
   644.5 2465.62   664.2 2465.45   683.9 2467.68   708.5 2473.11     738 2473.48
     758 2475.96     818 2490.64     853 2501.55     888 2506.64     908 2507.64
     943 2516.75   967.9 2520.34   992.9 2525.94  1027.9 2528.46  1062.9 2535.05
#Mann= 3 , 0 , 0
       0      .1       0   553.2    .045       0   568.2      .1       0
Bank Sta=553.2,568.2
XS Rating Curve= 0 ,0
Exp/Cntr=0.3,0.1

Type RM Length L Ch R = 1 ,16433.1 ,285.3,285.3,284.2
XS GIS Cut Line= 4
     1883148.785      186485.776      1883095.93      186878.138
     1883100.019      187242.134     1883204.425      187586.636
#Sta/Elev= 30
       0 2569.11    19.8 2563.21      94 2547.46   158.4 2532.31   202.9 2520.33
   257.3 2508.75   282.1 2505.32   336.5 2503.22   410.9 2496.23   440.8 2487.56
   485.7 2471.44   515.6 2456.74   554.2 2454.58   569.2  2452.4   575.4 2452.04
   600.4 2455.57   655.2 2456.78   769.9 2465.64   869.9 2483.52   884.9 2487.66
   904.9 2495.77   944.9  2507.6   969.9  2519.2   994.9 2528.77  1019.9 2533.75
  1034.9 2534.37  1049.9  2537.1  1084.9 2561.13  1104.9  2567.9  1119.9 2570.12
#Mann= 3 , 0 , 0
       0      .1       0   554.2    .045       0   569.2      .1       0
Bank Sta=554.2,569.2
XS Rating Curve= 0 ,0
Exp/Cntr=0.3,0.1

Type RM Length L Ch R = 1 ,16147.8 ,484.5,513.5,502.1
XS GIS Cut Line= 4
     1882870.988      186460.974        1882826.      186878.138
     1882870.988      187209.415     1883022.313      187610.219
#Sta/Elev= 30
       0 2579.94      35 2578.48   114.9 2568.91   174.8 2558.87   274.7 2545.97
   339.7 2533.53   374.6    2522   444.5  2496.1   449.5 2493.96   459.5 2486.68
   464.5 2484.45   484.4 2480.32   524.4 2466.07   552.9 2452.56   559.3  2451.4
   567.9 2451.68   614.2 2454.88   659.1 2456.32   674.1 2457.91     714 2458.94
   793.8 2466.66   913.3 2480.29   953.2  2488.2    1003 2502.23  1057.8 2515.28
  1082.7 2524.22  1107.6 2526.59  1117.6 2530.23  1147.4 2545.83  1182.3 2554.41
#Mann= 3 , 0 , 0
       0      .1       0   552.9    .045       0   567.9      .1       0
Bank Sta=552.9,567.9
XS Rating Curve= 0 ,0
Exp/Cntr=0.3,0.1

Type RM Length L Ch R = 1 ,15634.3 ,484.9,473.5,460.5
XS GIS Cut Line= 4
      1882454.81      186526.252     1882445.645      186788.161
     1882453.825      187238.044     1882641.957      187704.285
#Sta/Elev= 30
       0 2485.71    79.1 2480.36   108.8 2474.72   128.6 2476.17   153.3 2474.75
     178 2479.48   282.1 2475.25   302.1 2473.18   352.1 2459.68   382.1 2455.78
     422 2452.85   542.1 2450.28     552 2450.05   557.1 2450.07     632 2452.38
     652 2457.99     677 2470.42     687 2471.72   771.8 2495.12   811.6 2507.64
   836.5 2510.49   871.3 2522.96   901.2 2526.91   921.1 2532.48  1010.7 2539.41
  1100.3 2551.99  1130.2  2559.3  1155.1 2570.44  1189.9 2569.85  1214.8 2582.51
#Mann= 3 , 0 , 0
       0      .1       0   542.1    .045       0   557.1      .1       0
Bank Sta=542.1,557.1
XS Rating Curve= 0 ,0
Exp/Cntr=0.3,0.1

Type RM Length L Ch R = 1 ,15160.8 ,362.9,367.3,371.7
XS GIS Cut Line= 4
     1881864.888        186571.4     1881938.505      187025.372
     1882134.817      187287.122     1882396.567      187651.117
#Sta/Elev= 30
       0 2627.57      40 2615.02      60 2610.18      90 2607.78     105 2605.47
     185 2601.01     215 2594.72     230 2589.76   319.9 2551.58   334.9 2547.46
   374.9 2533.22   429.9 2519.68   459.9 2510.54   509.5 2484.48   519.4 2476.94
   529.3 2472.04   544.2 2469.91   594.9 2456.88   609.9 2454.42   623.5    2453
   653.2 2452.96   702.8 2455.35     822 2471.33   896.7 2477.85   936.5  2483.2
  1041.2 2492.76  1140.8 2504.98  1170.7 2505.62  1185.6 2508.81  1235.4 2524.41
#Mann= 3 , 0 , 0
       0      .1       0   594.9    .045       0   609.9      .1       0
Bank Sta=594.9,609.9
XS Rating Curve= 0 ,0
Exp/Cntr=0.3,0.1

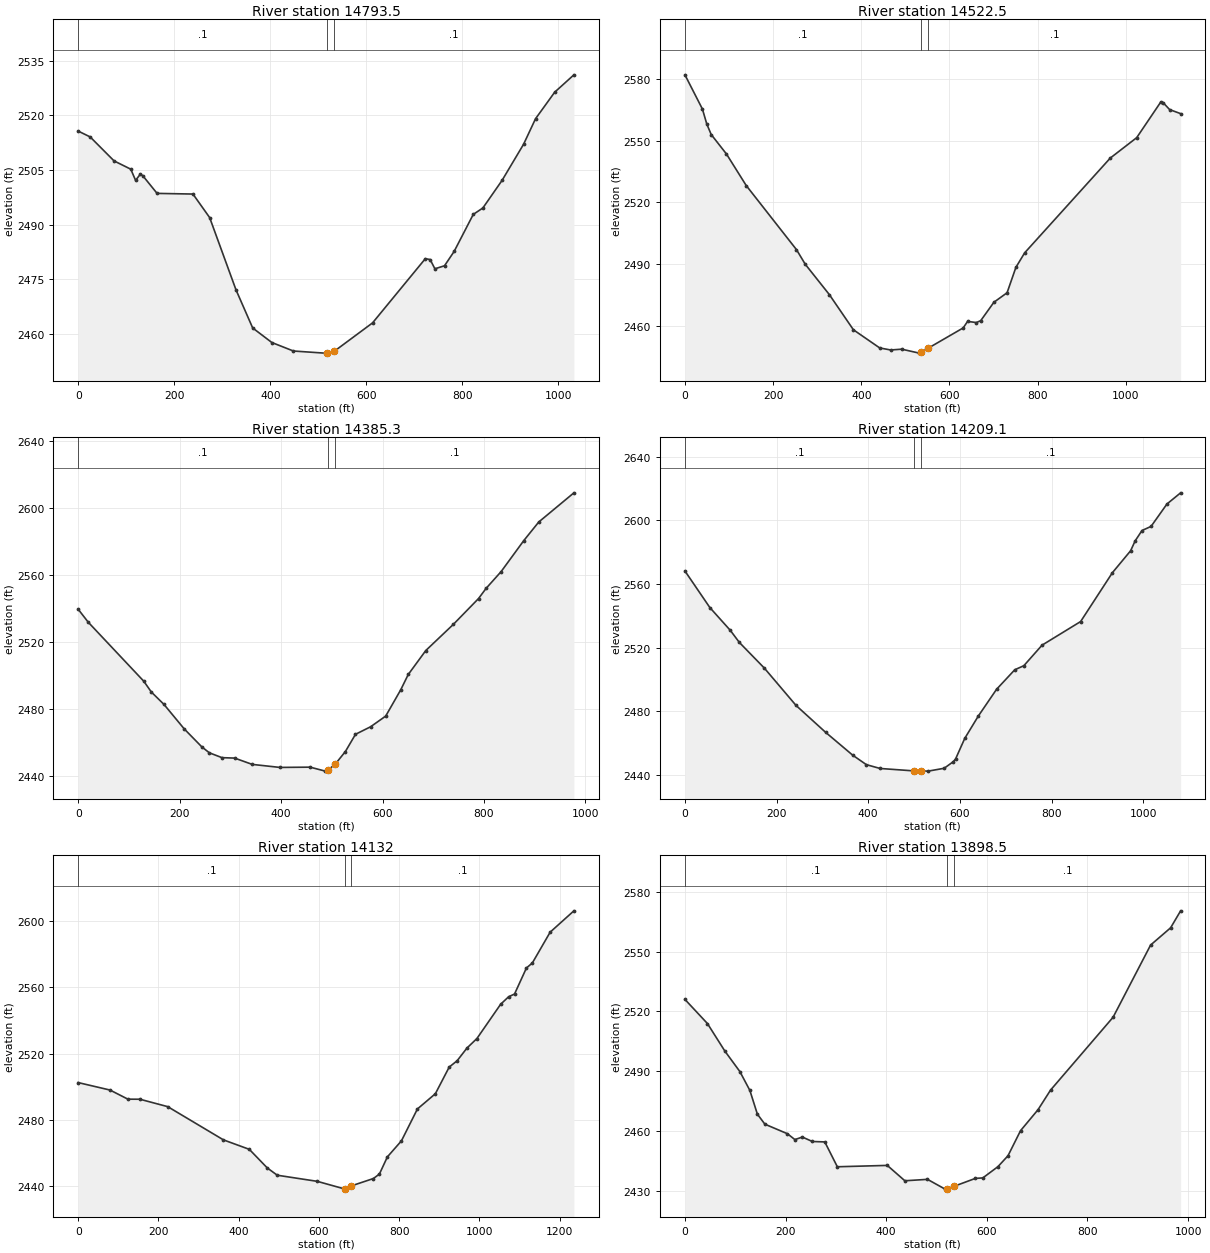
Type RM Length L Ch R = 1 ,14793.5 ,274,271.1,268.2
XS GIS Cut Line= 4
     1881607.228      186996.743     1881918.056      187291.212
     1882044.841      187540.692     1882286.141      187757.453
#Sta/Elev= 30
       0 2515.66    24.9 2514.06    74.7 2507.48   109.5 2505.21   119.5 2502.15
   129.4 2503.84   134.4 2503.44   164.3 2498.57     239 2498.39   273.8 2491.93
   328.6 2472.13   363.4 2461.66   403.3 2457.67   448.2 2455.34   513.1 2454.76
   518.6 2454.76   533.6  2455.3   613.1 2463.06     723 2480.67     733 2480.42
   742.9 2477.89   762.9 2478.72   782.9 2482.64   822.8 2492.81   842.8 2494.57
   882.7 2502.12   927.6 2512.05   952.5 2519.05   992.4 2526.33  1032.4 2531.09
#Mann= 3 , 0 , 0
       0      .1       0   518.6    .045       0   533.6      .1       0
Bank Sta=518.6,533.6
XS Rating Curve= 0 ,0
Exp/Cntr=0.3,0.1

Type RM Length L Ch R = 1 ,14522.5 ,116.5,137.2,137.3
XS GIS Cut Line= 4
     1881380.487      187093.173     1881652.216      187368.919
     1881842.425      187649.179     1882133.487      187921.575
#Sta/Elev= 30
       0 2582.02    39.7 2565.36    49.6 2558.08    59.6 2552.98    94.3 2543.48
     139 2528.17   253.1 2496.96     273 2489.85   327.6  2475.1   382.2 2457.98
   441.9 2449.14   466.8 2448.15   491.7 2448.54   531.6 2446.62   536.5 2447.09
   551.5 2448.98   631.2 2458.88   641.2 2462.05   661.1  2461.5     671 2462.41
   700.9 2471.37   730.8 2475.99   750.8 2488.35   770.7 2495.42     965 2541.54
  1024.8 2551.44  1079.6 2568.84  1084.6 2568.52  1099.6  2565.1  1124.5 2563.14
#Mann= 3 , 0 , 0
       0      .1       0   536.5    .045       0   551.5      .1       0
Bank Sta=536.5,551.5
XS Rating Curve= 0 ,0
Exp/Cntr=0.3,0.1

Type RM Length L Ch R = 1 ,14385.3 ,194.6,176.2,177.7
XS GIS Cut Line= 4
     1881389.892      187209.304     1881579.557       187452.42
     1881733.013      187678.294     1881967.508      187997.276
#Sta/Elev= 30
       0 2539.36    19.9  2531.6   129.3 2496.42   144.2 2489.98   169.1 2482.59
   208.9 2468.01   243.7 2457.25   258.6  2453.7   283.5 2450.81   308.4 2450.55
   343.1 2446.79   397.7 2444.98   457.3 2445.14   487.1 2442.77   491.6 2443.24
   506.6 2446.88   526.8 2454.48   546.7 2464.75   576.4 2469.23   606.2  2475.6
   635.8 2491.25   650.7 2500.44   685.3 2514.74   739.8  2530.4   789.3 2545.77
   804.1  2551.8   833.8 2561.84   878.3 2580.27     908 2591.44   977.3 2608.85
#Mann= 3 , 0 , 0
       0      .1       0   491.6    .045       0   506.6      .1       0
Bank Sta=491.6,506.6
XS Rating Curve= 0 ,0
Exp/Cntr=0.3,0.1

Type RM Length L Ch R = 1 ,14209.1 ,79.3,77.1,74.9
XS GIS Cut Line= 4
      1881300.49      187172.606     1881465.758       187521.39
     1881577.809      187721.804     1881889.427      188068.281
#Sta/Elev= 30
       0 2568.12    54.4 2545.11      99 2530.79   118.8 2523.18   173.2 2507.08
   242.5 2483.57   306.8 2466.73   366.2 2452.29   395.9 2446.36   425.9 2443.96
   499.9 2442.43   514.9 2442.34   530.7 2442.29   565.6 2444.08   585.6 2448.23
   590.6 2449.97   610.6  2462.9   640.4 2477.02     680 2493.74   719.7 2506.01
   739.5 2508.56   779.2 2521.47   863.4 2536.32   932.8 2567.06   972.5 2580.83
   982.4 2587.05   997.3 2593.54  1017.1 2596.14  1051.8 2610.23  1081.6 2617.24
#Mann= 3 , 0 , 0
       0      .1       0   499.9    .045       0   514.9      .1       0
Bank Sta=499.9,514.9
XS Rating Curve= 0 ,0
Exp/Cntr=0.3,0.1

Type RM Length L Ch R = 1 ,14132   ,237.6,233.4,229.1
XS GIS Cut Line= 4
     1880965.648      187247.875     1881345.302      187501.154
     1881578.494      187837.528     1881769.094      188154.834
#Sta/Elev= 30
       0 2502.57    79.4 2498.07     124 2492.58   153.8 2492.55   223.2 2488.08
   362.1 2468.07   426.6 2462.37   471.4 2451.16   496.3 2446.78   596.2 2443.09
   665.3 2438.43     666 2438.41   680.3 2440.31   735.9 2444.79   750.9 2447.48
   770.8 2457.83   805.8 2467.47   845.7 2486.69   890.4 2495.85   924.9 2511.91
   944.6  2515.7   969.3  2523.4     994  2529.1  1053.2 2549.76    1073 2554.25
  1087.8 2555.91  1117.4 2571.57  1132.2 2574.61  1176.6 2593.16  1235.8 2606.01
#Mann= 3 , 0 , 0
       0      .1       0   665.3    .045       0   680.3      .1       0
Bank Sta=665.3,680.3
XS Rating Curve= 0 ,0
Exp/Cntr=0.3,0.1

Type RM Length L Ch R = 1 ,13898.5 ,135.7,128.5,121.3
XS GIS Cut Line= 4
     1880916.063      187455.753     1881207.037      187740.537
     1881388.638      187897.374     1881654.849      188105.803
#Sta/Elev= 30
       0 2525.99    44.7  2513.9    79.4 2500.08   109.2 2489.82   129.1 2480.36
     144 2468.47   158.9 2463.45   203.6 2458.67   218.5 2455.73   233.4 2456.99
   253.2 2454.77     278 2454.55   302.9  2442.1   402.2 2442.78   437.1 2435.08
   482.1 2435.79   517.1 2430.89   520.6    2431   535.6 2432.37   577.1 2436.26
   592.1 2436.52   622.1 2442.15   642.1 2447.62     667 2460.18   701.8 2470.71
   726.6 2480.51     851 2517.06   925.5 2553.23   965.3 2561.88   985.2 2570.39
#Mann= 3 , 0 , 0
       0      .1       0   520.6    .045       0   535.6      .1       0
Bank Sta=520.6,535.6
XS Rating Curve= 0 ,0
Exp/Cntr=0.3,0.1

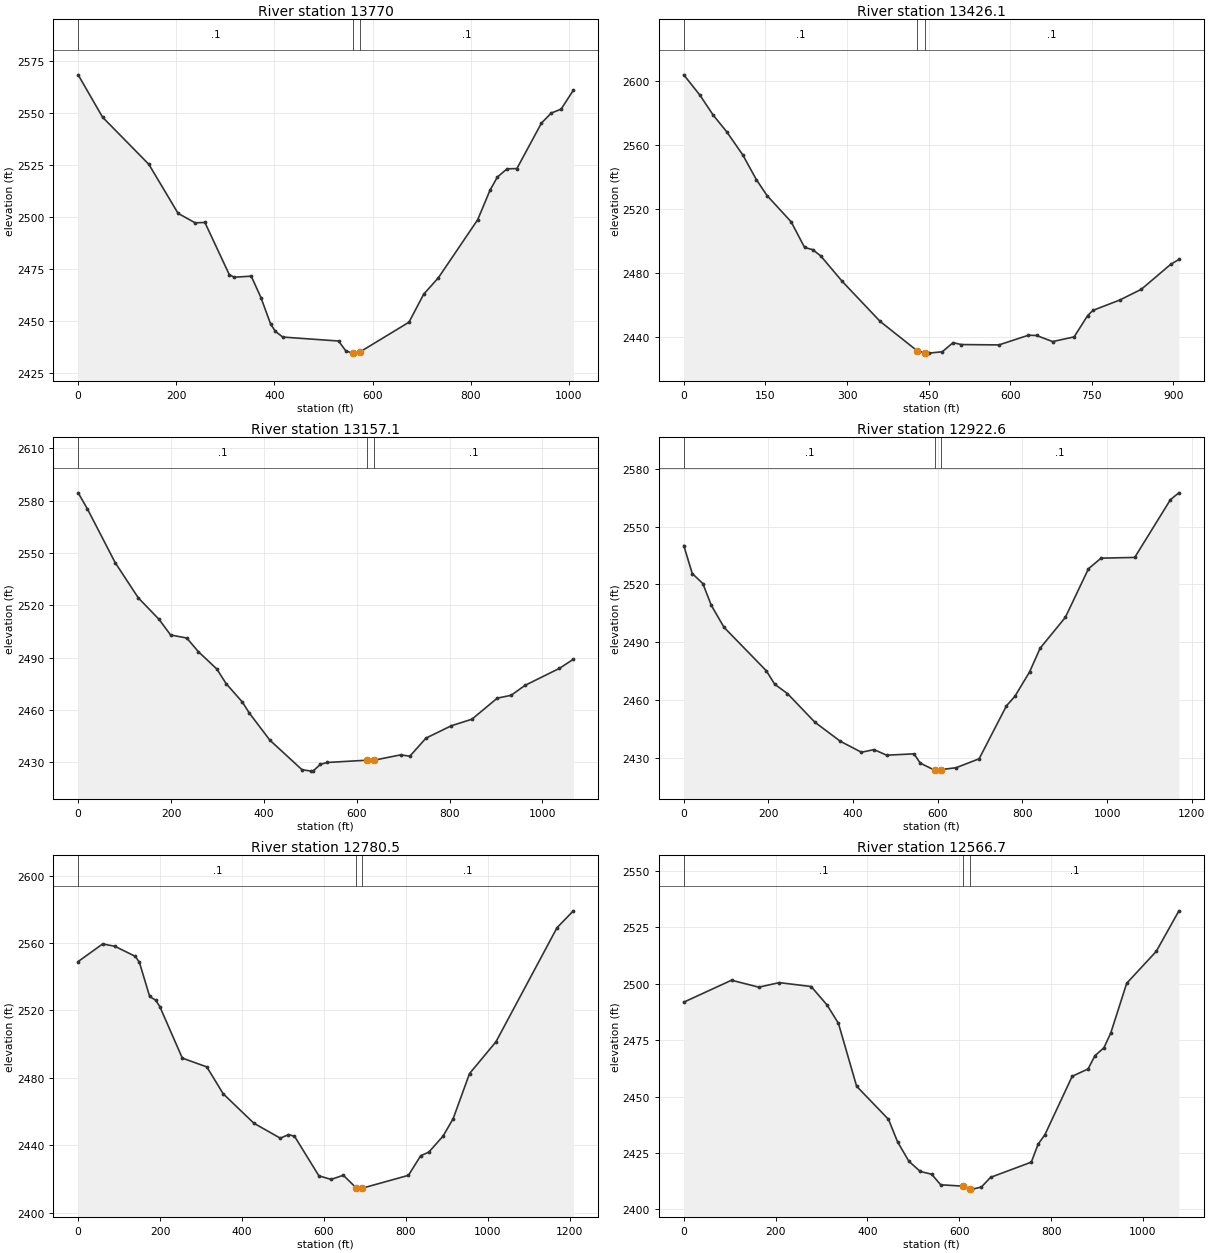
Type RM Length L Ch R = 1 ,13770   ,352.8,343.9,335
XS GIS Cut Line= 4
      1880789.26      187622.489     1881067.369       187839.25
     1881349.568      187982.394     1881611.318      188199.156
#Sta/Elev= 30
       0 2568.58    49.7 2548.18     144 2525.49   203.6 2501.86   238.4  2497.3
   258.2 2497.49   307.9 2472.37   317.8 2471.11   352.6 2471.62   372.4 2461.31
   392.2 2448.51     402 2444.99   416.9 2442.29   530.6 2440.38   545.4 2435.62
   559.1 2434.58   560.3 2434.55   574.1 2435.11     674 2449.44     704 2462.92
     734 2470.86     814 2498.78     839 2512.92     854 2519.31   873.9 2523.31
   893.9 2523.44   943.9 2545.31   963.9 2550.18   983.9 2552.04  1008.9 2561.15
#Mann= 3 , 0 , 0
       0      .1       0   559.1    .045       0   574.1      .1       0
Bank Sta=559.1,574.1
XS Rating Curve= 0 ,0
Exp/Cntr=0.3,0.1

Type RM Length L Ch R = 1 ,13426.1 ,264.9,268.9,274.8
XS GIS Cut Line= 4
     1880649.354      187976.578     1880873.277      188138.586
     1881125.465      188163.247     1881444.209      188370.628
#Sta/Elev= 30
       0 2603.62    29.6 2590.98    54.3 2578.39      79 2568.05   108.6 2553.57
   133.3 2538.28     153 2528.29   197.4 2511.87   222.1 2495.86   236.9  2494.5
   251.7 2490.62   291.3 2474.68   360.8 2449.76   428.5 2431.52   443.5 2430.07
   450.3 2429.93   475.1 2430.79     495 2436.48   509.9 2435.28   579.2 2435.06
   633.5 2441.11   648.3 2440.95   677.9 2437.14   717.4 2440.06   742.1 2453.29
     752 2456.61   801.4 2463.09   840.9 2469.77   895.2 2485.43     910 2488.39
#Mann= 3 , 0 , 0
       0      .1       0   428.5    .045       0   443.5      .1       0
Bank Sta=428.5,443.5
XS Rating Curve= 0 ,0
Exp/Cntr=0.3,0.1

Type RM Length L Ch R = 1 ,13157.1 ,229.9,234.5,244.2
XS GIS Cut Line= 4
     1880559.711      188055.093     1880893.401      188253.718
     1881262.844      188363.623     1881484.533      188554.972
#Sta/Elev= 30
       0 2584.55    19.9 2575.32    79.7 2544.51   129.4 2524.33   174.2 2511.95
   199.1    2503     234 2501.23   258.9 2493.42   298.7 2483.46   318.6 2475.11
   353.5 2464.57   368.4 2458.28     413 2442.62   482.2 2425.68     502 2424.87
   506.9 2425.13   521.8 2428.77   536.6 2429.84   623.1 2431.15   638.1 2431.19
   694.7  2434.2   714.5 2433.44   749.1 2443.79   803.6 2450.88   848.2 2454.65
   902.8 2466.76   932.6 2468.37   962.4 2474.05  1036.8 2483.86  1066.6 2489.04
#Mann= 3 , 0 , 0
       0      .1       0   623.1    .045       0   638.1      .1       0
Bank Sta=623.1,638.1
XS Rating Curve= 0 ,0
Exp/Cntr=0.3,0.1

Type RM Length L Ch R = 1 ,12922.6 ,135.4,142.1,149.3
XS GIS Cut Line= 4
     1880513.561       188279.85      1880901.16      188412.887
     1881140.668      188614.141     1881562.591      188762.102
#Sta/Elev= 30
       0  2540.2      20 2525.66      45 2520.47      65 2509.17      95 2497.75
   194.9 2475.19   214.9 2468.16   244.9 2463.32   309.8 2448.44   369.8 2438.56
   419.7 2432.84   449.5 2434.21   479.3 2431.32   543.9 2432.01   558.8 2427.18
   593.2 2423.47   598.5 2423.04   608.2 2423.86   643.2  2424.8   697.8 2429.45
   762.4 2456.98   782.2 2461.84     817 2474.58   841.9 2486.86   901.5 2502.91
   956.1 2528.14   985.9 2533.64  1065.4 2534.01  1149.9 2564.06  1169.8 2567.56
#Mann= 3 , 0 , 0
       0      .1       0   593.2    .045       0   608.2      .1       0
Bank Sta=593.2,608.2
XS Rating Curve= 0 ,0
Exp/Cntr=0.3,0.1

Type RM Length L Ch R = 1 ,12780.5 ,224.3,213.8,202.7
XS GIS Cut Line= 4
     1880367.991        188307.8     1880806.006      188404.673
     1880969.472      188671.405     1881322.841      188945.343
#Sta/Elev= 30
       0 2549.03    59.8 2559.49    89.7 2558.08   139.6  2552.1   149.5 2548.51
   174.5  2528.3   189.4 2526.05   199.4  2522.2   254.2 2491.69     314 2486.47
   353.9 2470.53   428.7 2453.05   493.3 2444.14   513.2 2446.23     528 2445.32
   587.6 2421.77   617.4 2419.65   647.2 2422.12     679 2414.55     682 2413.88
     694 2414.49   806.2 2422.07     836 2433.72   855.8 2435.84   890.6 2445.36
   915.4 2455.79   955.2 2482.48  1019.8 2501.39  1168.8 2569.12  1208.6 2579.15
#Mann= 3 , 0 , 0
       0      .1       0     679    .045       0     694      .1       0
Bank Sta=679,694
XS Rating Curve= 0 ,0
Exp/Cntr=0.3,0.1

Type RM Length L Ch R = 1 ,12566.7 ,275.8,277.2,277.9
XS GIS Cut Line= 4
      1880298.48      188428.187     1880715.643      188685.847
     1880948.764      188824.901     1881230.963      188968.046
#Sta/Elev= 30
       0 2491.89     104 2501.61   163.4 2498.53     208 2500.55   277.4 2498.82
     312 2490.64   336.8  2482.5   376.4 2454.62   445.8 2439.95   465.6 2429.97
   490.3 2421.34     515 2416.85   539.7 2415.63   559.4 2410.95   608.7 2410.33
   623.7 2409.09   628.5 2409.02   648.2 2409.96     668 2414.23   756.8 2420.98
   771.6 2428.95   786.5 2433.19   845.8 2459.03   880.4 2462.29   895.3 2468.14
     915  2471.7   929.9 2478.28   964.5 2500.27  1028.8 2514.39  1078.2 2532.37
#Mann= 3 , 0 , 0
       0      .1       0   608.7    .045       0   623.7      .1       0
Bank Sta=608.7,623.7
XS Rating Curve= 0 ,0
Exp/Cntr=0.3,0.1

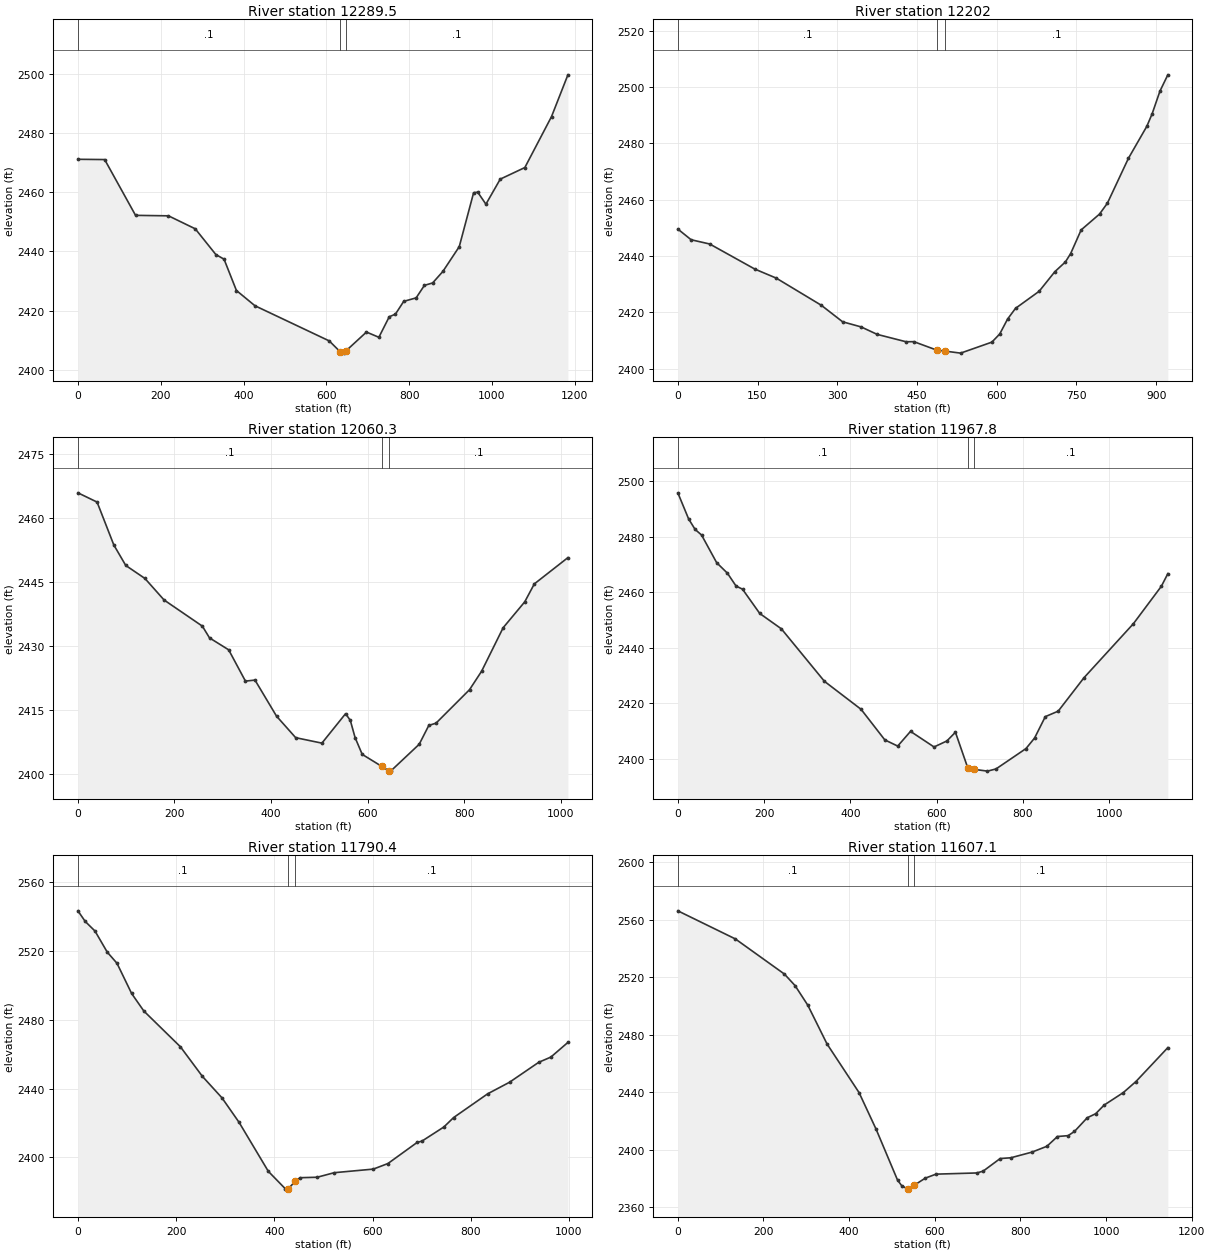
Type RM Length L Ch R = 1 ,12289.5 ,78.8,87.5,96.3
XS GIS Cut Line= 4
     1880204.638      188464.171     1880570.985      188842.906
     1880825.262      189019.999     1881158.496      189114.892
#Sta/Elev= 30
       0 2471.12    64.6 2471.03   139.2 2452.18   218.7 2452.02   283.4 2447.63
   333.1 2438.94   352.9 2437.37   382.8 2426.79   427.5 2421.64   606.9 2409.76
   632.8 2406.17   641.9 2405.63   647.8 2406.45   696.8 2412.75   726.8 2410.98
   751.8 2417.91   766.8 2418.81   786.8 2423.12   816.8  2424.3   836.8 2428.53
   856.6 2429.34   881.3 2433.22   920.9  2441.6   955.6 2459.83   965.5 2460.01
   985.3 2455.95  1019.9 2464.42  1079.3 2468.33  1143.7 2485.54  1183.3 2499.66
#Mann= 3 , 0 , 0
       0      .1       0   632.8    .045       0   647.8      .1       0
Bank Sta=632.8,647.8
XS Rating Curve= 0 ,0
Exp/Cntr=0.3,0.1

Type RM Length L Ch R = 1 ,12202   ,130.6,141.7,152.6
XS GIS Cut Line= 4
     1880301.612      188610.894     1880573.678      188910.875
     1880678.358      189052.285     1880953.707      189253.424
#Sta/Elev= 30
       0 2449.54      25 2445.74      60 2444.23     145 2435.31     185 2432.13
     270 2422.46     310  2416.6     345 2414.77     375 2412.13   429.4 2409.51
   444.1 2409.54   487.3 2406.53   502.3  2406.2     532 2405.47   590.8 2409.37
   605.6 2412.26   620.4 2417.57   635.3 2421.37   679.8 2427.44   709.4 2434.41
   729.2 2437.86   739.1 2440.85   758.8 2449.23   793.4 2454.86   808.2 2458.73
   847.8 2474.68   882.4 2486.04   892.3 2490.44   907.1 2498.55   921.9 2504.32
#Mann= 3 , 0 , 0
       0      .1       0   487.3    .045       0   502.3      .1       0
Bank Sta=487.3,502.3
XS Rating Curve= 0 ,0
Exp/Cntr=0.3,0.1

Type RM Length L Ch R = 1 ,12060.3 ,92.4,92.5,92.7
XS GIS Cut Line= 4
     1880212.359      188570.124     1880519.842      188933.326
     1880548.734      189137.627     1880742.716      189407.965
#Sta/Elev= 30
       0 2465.93    39.7 2463.76    74.4  2453.7    99.1 2448.91   138.8 2445.86
   178.5 2440.81   257.8 2434.68   272.6 2431.93   312.3 2429.13     347  2421.8
   366.8 2422.04   411.4 2413.59   451.1 2408.54   505.4 2407.26   554.5 2414.17
   564.3 2412.58   574.1 2408.58   588.9 2404.63   629.7 2401.79   644.7 2400.74
   647.8  2400.7     707    2407   726.9 2411.42   741.8 2411.94   811.3  2419.8
   836.2 2424.11   880.9 2434.32   925.6 2440.38   945.4 2444.58    1015 2450.74
#Mann= 3 , 0 , 0
       0      .1       0   629.7    .045       0   644.7      .1       0
Bank Sta=629.7,644.7
XS Rating Curve= 0 ,0
Exp/Cntr=0.3,0.1

Type RM Length L Ch R = 1 ,11967.8 ,197.2,177.4,169.1
XS GIS Cut Line= 4
     1880106.257      188575.421     1880445.714      188935.327
     1880462.073      189242.065     1880658.385      189511.994
#Sta/Elev= 30
       0 2495.76      25 2486.37      40  2482.6      55 2480.58      90 2470.63
   114.9 2466.86   134.9 2462.24   149.9  2461.1   189.9 2452.36   239.9 2446.85
   339.8 2427.96   424.8 2417.88   479.7  2406.9   509.6 2404.67   539.3 2409.96
   593.8 2404.35   623.6 2406.51   643.4 2409.65   671.7 2396.96   686.7  2396.3
   717.7 2395.66   737.5 2396.45   806.9 2403.77   826.8 2407.55   851.7 2415.26
   881.6 2417.23   941.4 2429.26    1056 2448.71  1120.7 2462.15  1135.7 2466.69
#Mann= 3 , 0 , 0
       0      .1       0   671.7    .045       0   686.7      .1       0
Bank Sta=671.7,686.7
XS Rating Curve= 0 ,0
Exp/Cntr=0.3,0.1

Type RM Length L Ch R = 1 ,11790.4 ,180.7,183.3,185.9
XS GIS Cut Line= 3
     1880041.391      188735.406     1880419.409      189216.186
     1880610.852      189551.852
#Sta/Elev= 30
       0 2543.35    14.9 2537.17    34.8 2531.59    59.7 2519.35    79.6 2512.85
   109.4 2495.28   134.2 2485.12   208.8 2464.29   253.6 2447.07   293.4 2434.61
   328.2 2420.38   387.8 2391.88   422.6 2381.69   427.6 2381.53     428  2381.6
     443  2386.2   452.5 2388.17   487.3 2388.44   522.1 2391.09   601.6 2393.17
   631.4 2396.41   690.9 2408.68   700.8 2409.46   745.4 2417.67   765.2 2423.14
   834.5 2436.94   879.1 2443.68   938.6 2455.28   963.3 2458.31     998 2466.84
#Mann= 3 , 0 , 0
       0      .1       0     428    .045       0     443      .1       0
Bank Sta=428,443
XS Rating Curve= 0 ,0
Exp/Cntr=0.3,0.1

Type RM Length L Ch R = 1 ,11607.1 ,116,113.7,111.4
XS GIS Cut Line= 4
     1879986.292      188657.996     1880037.642      189017.547
     1880282.409      189326.973     1880473.852      189662.638
#Sta/Elev= 30
       0 2566.16   134.3 2546.61   248.8 2522.17   273.6 2514.18   303.5 2500.48
   348.3 2473.56   423.1 2439.71   463.1 2414.11     513 2378.81     523 2374.78
   537.5 2372.54     538  2372.5   552.5  2375.3   577.9 2380.16   602.9 2382.93
   697.8 2383.75   712.8 2384.99   752.7 2393.79   777.6 2394.32   827.1 2398.27
   861.8 2402.31   886.5 2409.12   911.3 2409.71   926.2 2412.64   955.9 2422.14
   975.7 2424.98   995.5 2430.99  1040.1 2439.65  1069.8 2447.39  1144.2 2470.97
#Mann= 3 , 0 , 0
       0      .1       0   537.5    .045       0   552.5      .1       0
Bank Sta=537.5,552.5
XS Rating Curve= 0 ,0
Exp/Cntr=0.3,0.1

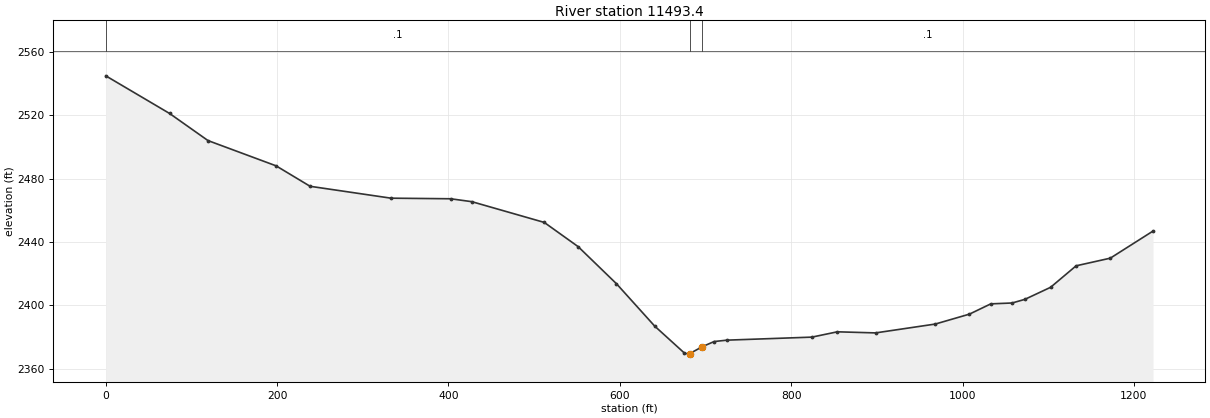
Type RM Length L Ch R = 1 ,11493.4 ,283.4,268.7,253.9
XS GIS Cut Line= 4
     1879781.335      188618.934     1879932.659      189097.445
     1880223.038      189396.004     1880405.179      189639.403
#Sta/Elev= 30
       0 2544.76    74.5 2521.02   119.3 2503.94   198.8 2488.01   238.5 2475.11
   332.9 2467.62   402.5 2467.25   427.3 2465.41   511.8 2452.34   551.4 2437.05
   596.1 2413.68   640.7 2386.97   675.4 2369.96   680.4  2369.3   681.4 2369.59
   696.4 2374.02   710.1 2377.24     725 2378.11   824.2 2380.02   853.9 2383.37
   898.5 2382.68   968.2 2388.26  1008.1 2394.52    1033 2400.99  1057.9 2401.54
  1072.8 2403.84  1102.8 2411.43  1132.6 2424.98  1172.5  2429.8  1222.4  2446.9
#Mann= 3 , 0 , 0
       0      .1       0   681.4    .045       0   696.4      .1       0
Bank Sta=681.4,696.4
XS Rating Curve= 0 ,0
Exp/Cntr=0.3,0.1