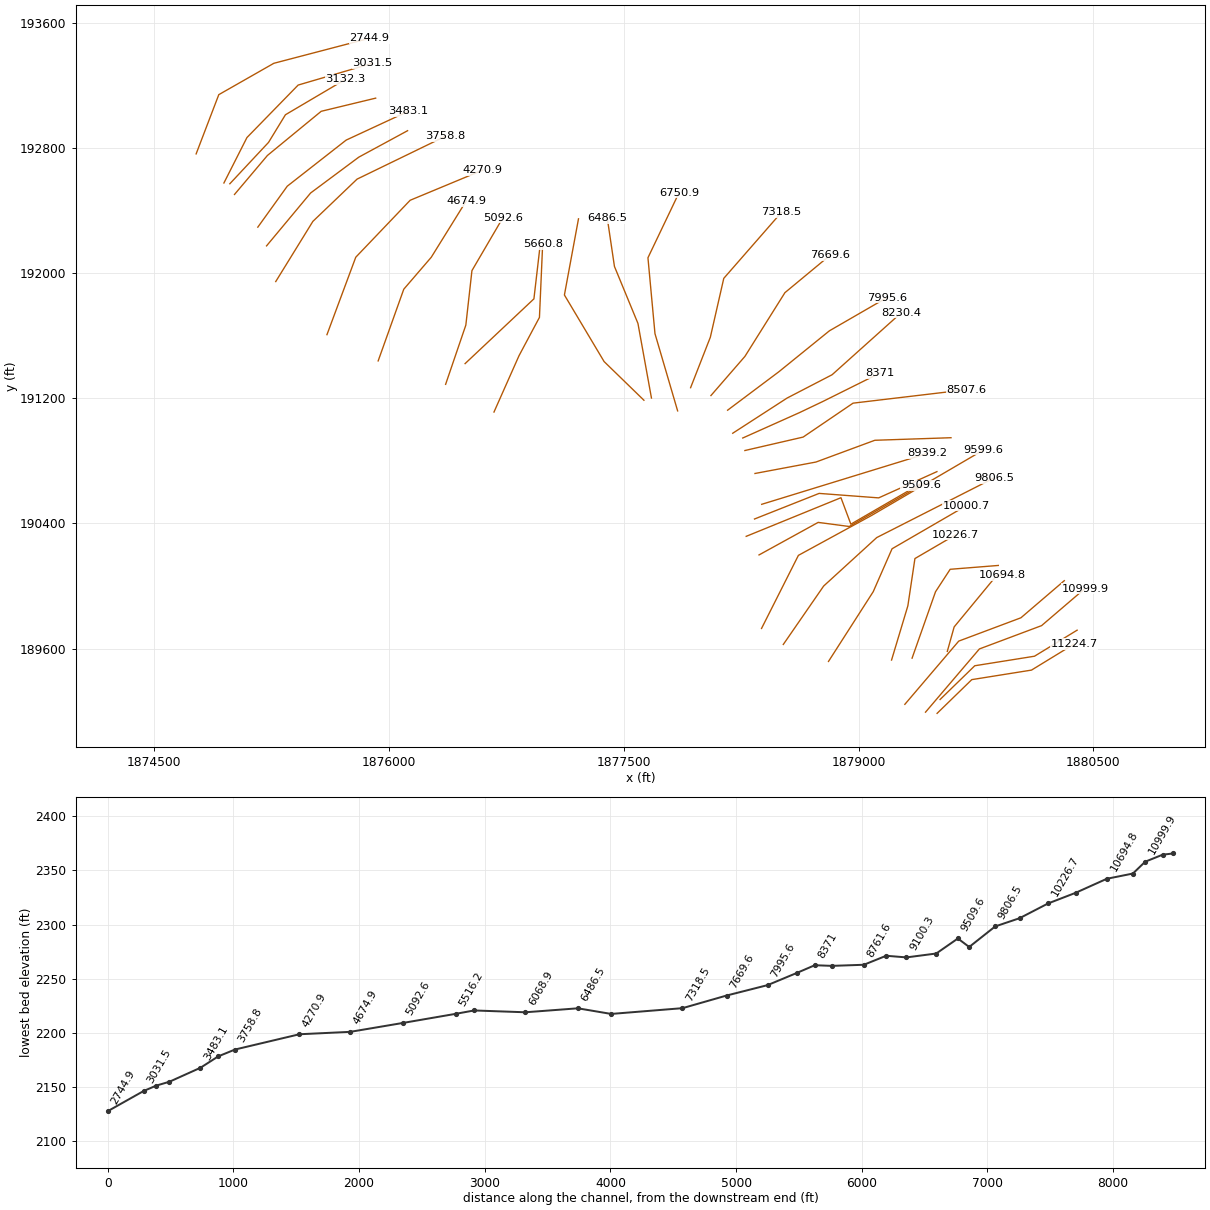
HEC-RAS study MilamFk2.prj: MilamFk2

--- MilamFk2.g01 (geometry) --- (continued)

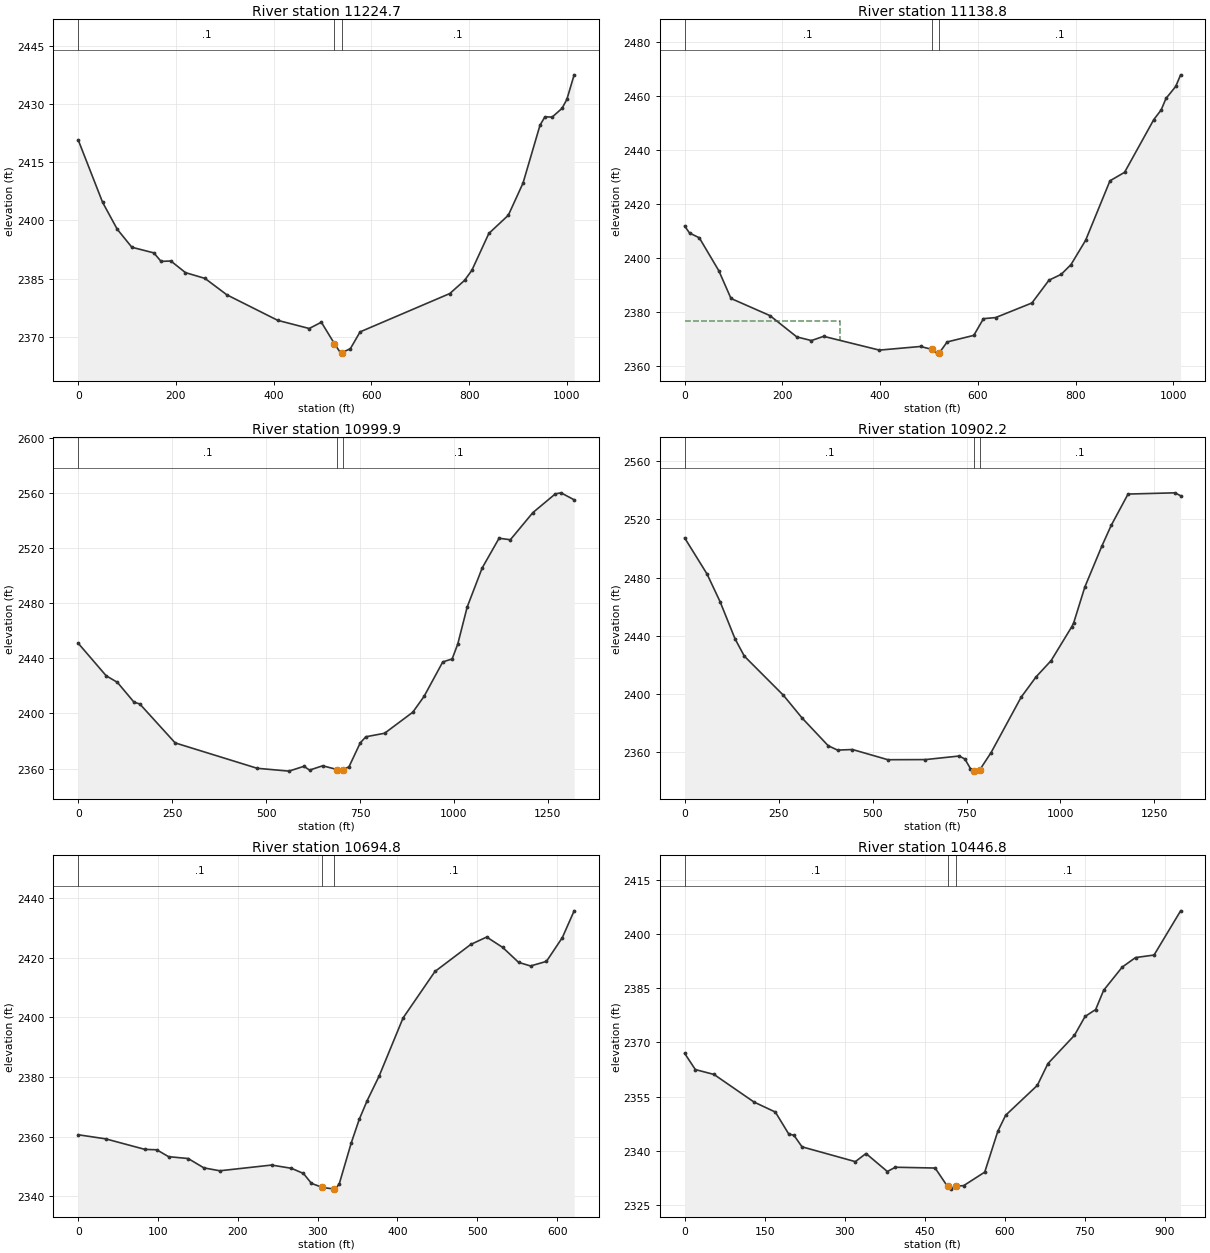
Type RM Length L Ch R = 1 ,11224.7 ,86.2,86,85.7
XS GIS Cut Line= 4
      1879502.07      189186.064     1879723.786      189401.737
     1880105.423      189462.618     1880377.797      189629.128
#Sta/Elev= 30
       0 2420.76    49.9 2404.68    79.8 2397.75   109.8 2393.09   154.7 2391.64
   169.6 2389.44   189.6 2389.55   219.5 2386.55   259.4 2385.06   304.3 2380.82
   408.4 2374.24   472.8 2372.14   497.6 2373.76   524.2 2368.27   537.2 2365.79
   539.2 2365.89     557 2366.94   576.9 2371.27   760.6 2381.16   790.6 2384.54
   805.5 2387.11   840.4 2396.65   880.3 2401.35   910.3 2409.62   945.2 2424.59
   955.2 2426.72   970.1 2426.66   990.1  2428.9    1000 2431.19    1015 2437.55
#Mann= 3 , 0 , 0
       0      .1       0   524.2    .045       0   539.2      .1       0
Bank Sta=524.2,539.2
XS Rating Curve= 0 ,0
Exp/Cntr=0.3,0.1

Type RM Length L Ch R = 1 ,11138.8 ,134.4,138.9,143.4
XS GIS Cut Line= 4
     1879521.197      189274.735     1879742.913      189490.409
      1880124.55       189551.29     1880396.924      189717.799
#Sta/Elev= 30
       0  2411.8      10  2409.2    29.9 2407.44    69.8 2395.23    94.8  2384.9
   174.6 2378.53   229.5 2370.62   259.4 2369.27   284.4 2370.84   398.5 2365.72
   482.7 2367.07   505.8    2366   517.4  2364.6   520.8 2364.61   537.2 2368.76
   591.7 2371.19   611.5  2377.4   636.3  2377.8   710.7 2383.23   745.6  2391.7
   770.6 2393.86   790.6 2397.47   820.5 2406.48   870.4  2428.6   900.3 2431.75
   960.1 2451.34   975.1  2454.9   985.1  2459.2    1005 2463.66    1015 2467.96
#Mann= 3 , 0 , 0
       0      .1       0   505.8    .045       0   520.8      .1       0
#XS Ineff= 2 , 0
          318.42 2376.65
Permanent Ineff=
       F       F
Bank Sta=505.8,520.8
XS Rating Curve= 0 ,0
Exp/Cntr=0.3,0.1

Type RM Length L Ch R = 1 ,10999.9 ,97.6,97.7,97.7
XS GIS Cut Line= 4
     1879428.155      189193.842     1879772.518      189597.806
      1880169.86      189746.809     1880446.871      189983.831
#Sta/Elev= 30
       0 2451.04    74.4  2427.4   104.2 2422.64   148.8 2408.12   163.7 2406.97
     258 2378.62   476.2 2360.18   560.8 2358.11   600.7 2361.61   615.7 2358.86
   650.6    2362   688.8 2359.27   703.8 2359.17   720.5 2361.22   750.5 2378.62
   765.5 2383.07   815.4 2385.64   890.3  2400.9   920.2 2412.34   970.2 2437.48
   995.1 2439.62  1010.1  2450.5  1035.1 2477.32    1075 2505.73    1120 2527.35
    1150 2526.25  1209.9 2545.96  1269.8 2559.59  1284.8 2560.34  1319.8 2555.28
#Mann= 3 , 0 , 0
       0      .1       0   688.8    .045       0   703.8      .1       0
#XS Ineff= 2 , 0
           650.4 2361.94
Permanent Ineff=
       F       F
Bank Sta=688.8,703.8
XS Rating Curve= 0 ,0
Exp/Cntr=0.3,0.1

Type RM Length L Ch R = 1 ,10902.2 ,195.6,207.4,219.2
XS GIS Cut Line= 4
     1879296.124      189243.918     1879640.486      189647.882
     1880037.828      189796.885     1880314.839      190033.906
#Sta/Elev= 30
       0 2507.18    59.5 2482.43    94.3 2463.41     134 2437.96   158.8 2426.06
   262.9 2399.18   312.5 2383.62     382  2364.6   406.8 2361.61   446.5 2362.01
   540.8 2355.01   640.7  2355.1   730.5 2357.55   745.5 2355.52   760.5 2348.93
     770 2347.21   770.5 2347.18     785 2347.96   815.4 2359.91   895.3 2397.87
   935.2 2411.87   975.2 2423.02  1030.1 2446.25  1035.1 2448.82    1065 2473.59
    1110 2501.47    1135 2515.77  1179.9  2537.3  1304.8 2538.14  1319.8 2536.12
#Mann= 3 , 0 , 0
       0      .1       0     770    .045       0     785      .1       0
Bank Sta=770,785
XS Rating Curve= 0 ,0
Exp/Cntr=0.3,0.1

Type RM Length L Ch R = 1 ,10694.8 ,245.6,248,250.3
XS GIS Cut Line= 4
      1879567.39      189582.207     1879611.142      189738.577
     1879881.275      190065.854      1879915.89      190068.411
#Sta/Elev= 30
       0  2360.6    34.4 2359.23    83.6 2355.69    98.4 2355.56   113.2 2353.25
   137.8 2352.62   157.5 2349.48   177.4 2348.51   242.3 2350.43   267.2 2349.34
   282.2 2347.61   292.2 2344.29   305.7 2342.94   320.7 2342.37   322.1 2342.35
   327.1 2344.13   342.1 2357.87   352.1 2365.76   362.1  2372.1     377 2380.29
     407  2399.8     447 2415.42   491.9  2424.5   511.8 2426.98   531.8 2423.51
   551.8 2418.48   566.8 2417.27   586.7 2418.81   606.6  2426.8   621.4 2435.78
#Mann= 3 , 0 , 0
       0      .1       0   305.7    .045       0   320.7      .1       0
Bank Sta=305.7,320.7
XS Rating Curve= 0 ,0
Exp/Cntr=0.3,0.1

Type RM Length L Ch R = 1 ,10446.8 ,216.7,220.1,229.8
XS GIS Cut Line= 4
     1879342.307       189538.91     1879492.075      189963.253
      1879585.68      190106.781     1879893.237      190131.308
#Sta/Elev= 30
       0 2366.96      20 2362.48      55 2361.13     130 2353.49     170 2350.72
     195 2344.67     205 2344.26     220 2341.09     320 2336.99     340 2339.24
     380 2334.26     395 2335.44   469.6 2335.22   492.8 2330.14     499 2329.38
   507.8 2330.15   523.4 2330.37   562.6 2334.09   587.1 2345.38   601.8 2349.83
   661.2  2358.1   681.1 2364.14   730.8 2371.96   750.7 2377.18   770.6  2379.1
   785.6 2384.44   820.4 2390.85   845.3 2393.49   880.1 2394.19   929.9 2406.43
#Mann= 3 , 0 , 0
       0      .1       0   492.8    .045       0   507.8      .1       0
Bank Sta=492.8,507.8
XS Rating Curve= 0 ,0
Exp/Cntr=0.3,0.1

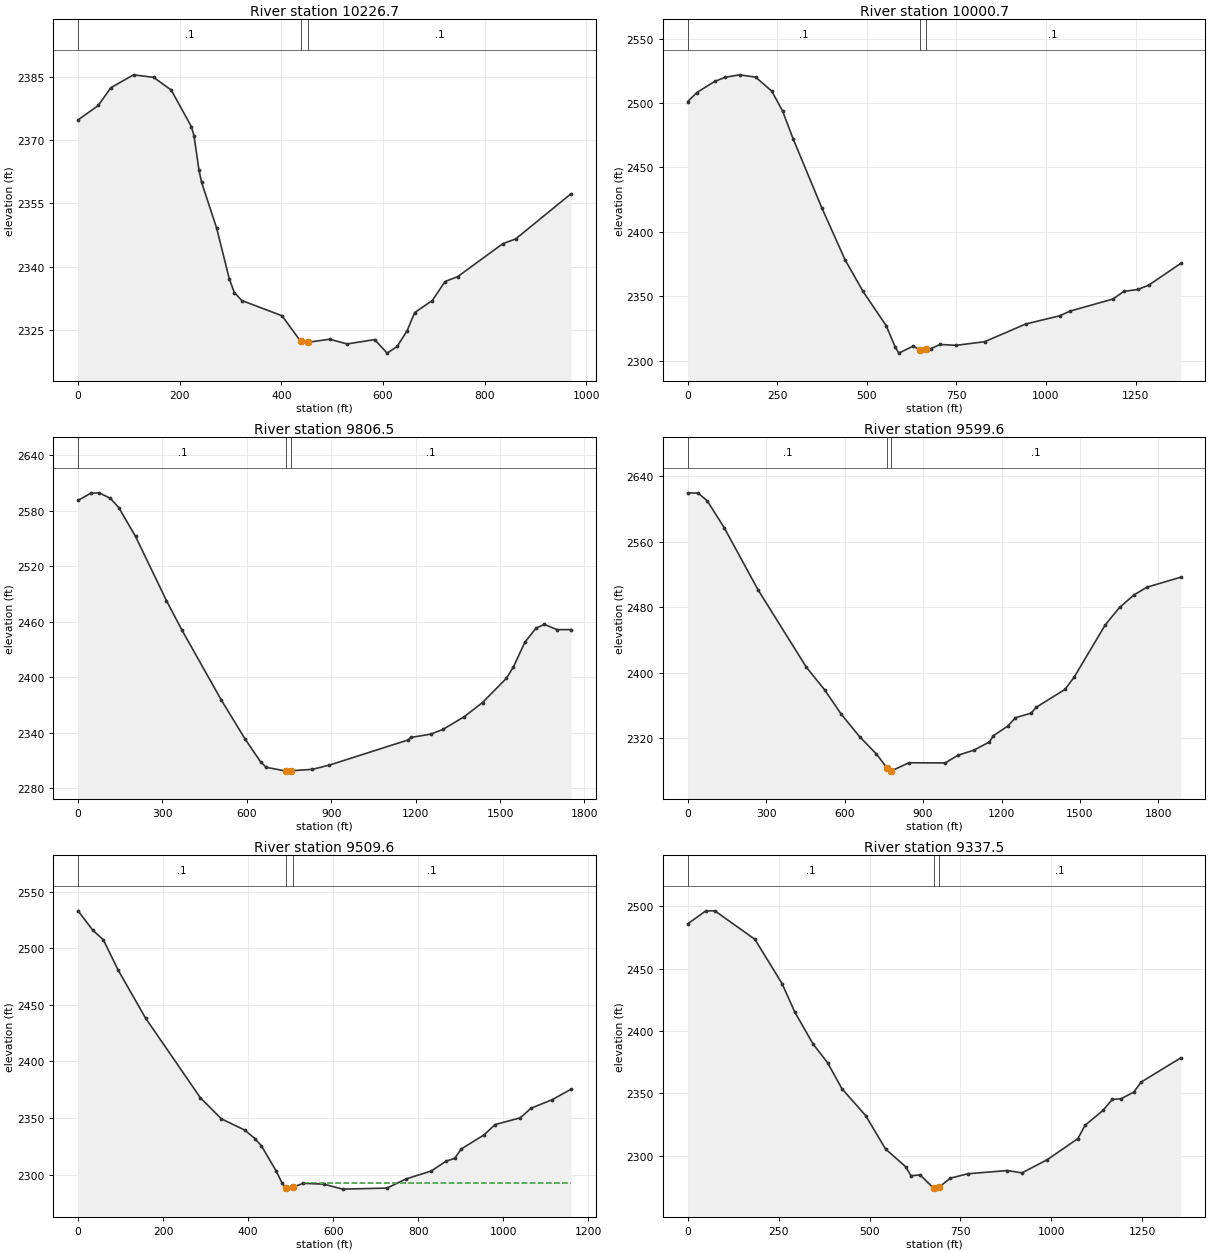
Type RM Length L Ch R = 1 ,10226.7 ,231.8,226,220.2
XS GIS Cut Line= 4
     1879211.138       189526.73     1879315.351      189873.343
     1879360.503      190175.393     1879622.072      190327.975
#Sta/Elev= 30
       0  2374.8    39.7 2378.24    64.5 2382.46   109.1 2385.51   148.7 2384.91
   183.4 2381.89   223.1 2373.19   228.1 2371.07     238 2362.85     243 2360.04
   272.7 2349.15   297.5 2337.16   307.4 2333.87   322.3 2331.97   401.4 2328.36
   437.9 2322.32   452.9 2322.08   494.9  2322.8   529.4 2321.68   583.6 2322.71
   608.2  2319.5   627.9 2321.08   647.6 2324.84   662.4 2329.13   697.1 2331.98
     722 2336.47   746.8 2337.63   836.1 2345.48     861 2346.58   970.2 2357.32
#Mann= 3 , 0 , 0
       0      .1       0   437.9    .045       0   452.9      .1       0
Bank Sta=437.9,452.9
XS Rating Curve= 0 ,0
Exp/Cntr=0.3,0.1

Type RM Length L Ch R = 1 ,10000.7 ,203.6,194.1,184.7
XS GIS Cut Line= 4
     1878808.174      189517.995     1879093.919      189963.421
      1879214.38       190237.96     1879687.821        190512.5
#Sta/Elev= 30
       0 2501.11      25 2508.05    74.9 2516.74   104.8    2520   144.8  2521.9
   189.7 2520.09   234.6 2509.27   264.6 2493.92   294.6 2472.02   374.4 2418.64
   439.3 2378.33   489.3 2353.85   554.2  2327.1   579.2 2310.68   589.2 2305.91
   629.1  2311.3   649.1  2308.4   664.1 2309.34   679.1 2309.38   704.1 2312.62
   749.1 2311.96     829 2314.78   943.4  2328.5    1038 2334.86  1067.8 2338.58
  1187.2  2347.9  1217.1 2353.79  1256.9 2355.35  1286.7 2358.64  1376.3 2375.56
#Mann= 3 , 0 , 0
       0      .1       0   649.1    .045       0   664.1      .1       0
Bank Sta=649.1,664.1
XS Rating Curve= 0 ,0
Exp/Cntr=0.3,0.1

Type RM Length L Ch R = 1 ,9806.5  ,212,206.9,201.8
XS GIS Cut Line= 4
     1878519.399       189626.51     1878777.358       189999.84
     1879116.516      190309.513     1879864.957      190689.868
#Sta/Elev= 30
       0 2591.33    44.9 2599.05    74.8 2599.54   114.7 2593.64   144.6 2583.56
   204.4 2552.31   314.2 2482.87     369 2451.11   508.7 2375.48   593.6 2333.13
   648.5 2308.44   668.4 2302.45   740.7 2298.31   743.3  2298.3   755.7 2298.64
   833.2 2300.28   893.1 2304.81  1172.9 2332.03  1182.9 2334.74  1252.9 2338.31
  1297.8 2343.55  1372.8 2357.27  1437.8 2372.57  1522.7 2398.82  1547.7  2411.2
  1587.7 2437.55  1627.7 2453.04  1657.6 2457.17  1702.6 2451.45  1752.6 2451.49
#Mann= 3 , 0 , 0
       0      .1       0   740.7    .045       0   755.7      .1       0
Bank Sta=740.7,755.7
XS Rating Curve= 0 ,0
Exp/Cntr=0.3,0.1

Type RM Length L Ch R = 1 ,9599.6  ,104.4,90,75.6
XS GIS Cut Line= 4
     1878380.345      189728.756     1878615.941      190195.793
     1879082.155      190450.092     1879799.519      190869.821
#Sta/Elev= 30
       0 2619.91    39.8  2619.6    74.7 2610.11   139.5 2577.26     269 2501.17
   453.4 2406.61   523.1    2379   587.6 2348.74   657.1 2321.57   721.6 2300.29
   762.8 2282.91   776.2  2279.3   777.8 2279.41   845.7 2289.52   984.7 2289.36
  1034.3 2298.86    1094  2304.9  1153.7 2315.05  1168.6  2322.6  1223.4 2334.37
  1253.2 2344.64    1313 2350.32  1332.9 2357.49  1442.4 2379.29  1477.2 2394.06
  1596.6 2458.33  1651.4 2479.67  1706.1  2494.9  1755.9  2504.4  1885.3 2516.66
#Mann= 3 , 0 , 0
       0      .1       0   762.8    .045       0   777.8      .1       0
Bank Sta=762.8,777.8
XS Rating Curve= 0 ,0
Exp/Cntr=0.3,0.1

Type RM Length L Ch R = 1 ,9509.6  ,197.3,172.1,142.9
XS GIS Cut Line= 4
     1878364.386      190198.594     1878742.226      190406.454
     1878941.019       190380.24     1879398.179      190643.564
#Sta/Elev= 30
       0 2533.04    34.7 2515.87    59.5 2507.42    94.2 2480.69   158.6 2438.33
   287.5 2367.94   337.1 2349.25   391.6 2339.38   416.4 2331.69   431.2 2325.32
   465.5 2303.45   480.2 2292.17   489.9 2287.92   489.9 2287.91   504.9 2288.74
     529 2292.32     578 2291.54     622 2287.16   726.3 2288.08   771.1 2296.14
   830.8 2303.25   865.7 2311.96   885.6 2314.26   900.5 2322.51   955.3 2335.27
   980.2 2344.16  1039.9 2350.18  1064.8 2358.59  1114.5 2366.14  1159.3 2375.46
#Mann= 3 , 0 , 0
       0      .1       0   489.9    .045       0   504.9      .1       0
#XS Ineff= 2 , 0
                          529.42         2292.32
Permanent Ineff=
       F       F
Bank Sta=489.9,504.9
XS Rating Curve= 0 ,0
Exp/Cntr=0.3,0.1

Type RM Length L Ch R = 1 ,9337.5  ,209.9,237.2,264.5
XS GIS Cut Line= 4
     1878282.272      190317.293     1878887.826      190564.199
     1878951.086      190394.992     1879402.081      190656.201
#Sta/Elev= 30
       0 2485.78    49.9 2496.22    74.9 2496.17   184.7 2473.42   259.6 2437.84
   294.5 2415.09   344.4 2389.68   384.4 2374.63   424.3 2353.65   489.2 2332.23
   544.1  2305.4     599 2291.32     614 2283.97     639 2284.67   676.3 2274.01
   683.2 2273.27   691.3 2274.93   722.3 2282.04   771.1 2285.62   879.3 2288.16
     919  2286.3   988.5 2296.82  1072.8 2313.72  1092.7 2324.42  1142.3 2336.44
  1167.2 2345.11    1192 2345.74  1226.7 2351.01  1246.6 2358.97  1355.8 2378.44
#Mann= 3 , 0 , 0
       0      .1       0   676.3    .045       0   691.3      .1       0
Bank Sta=676.3,691.3
XS Rating Curve= 0 ,0
Exp/Cntr=0.3,0.1

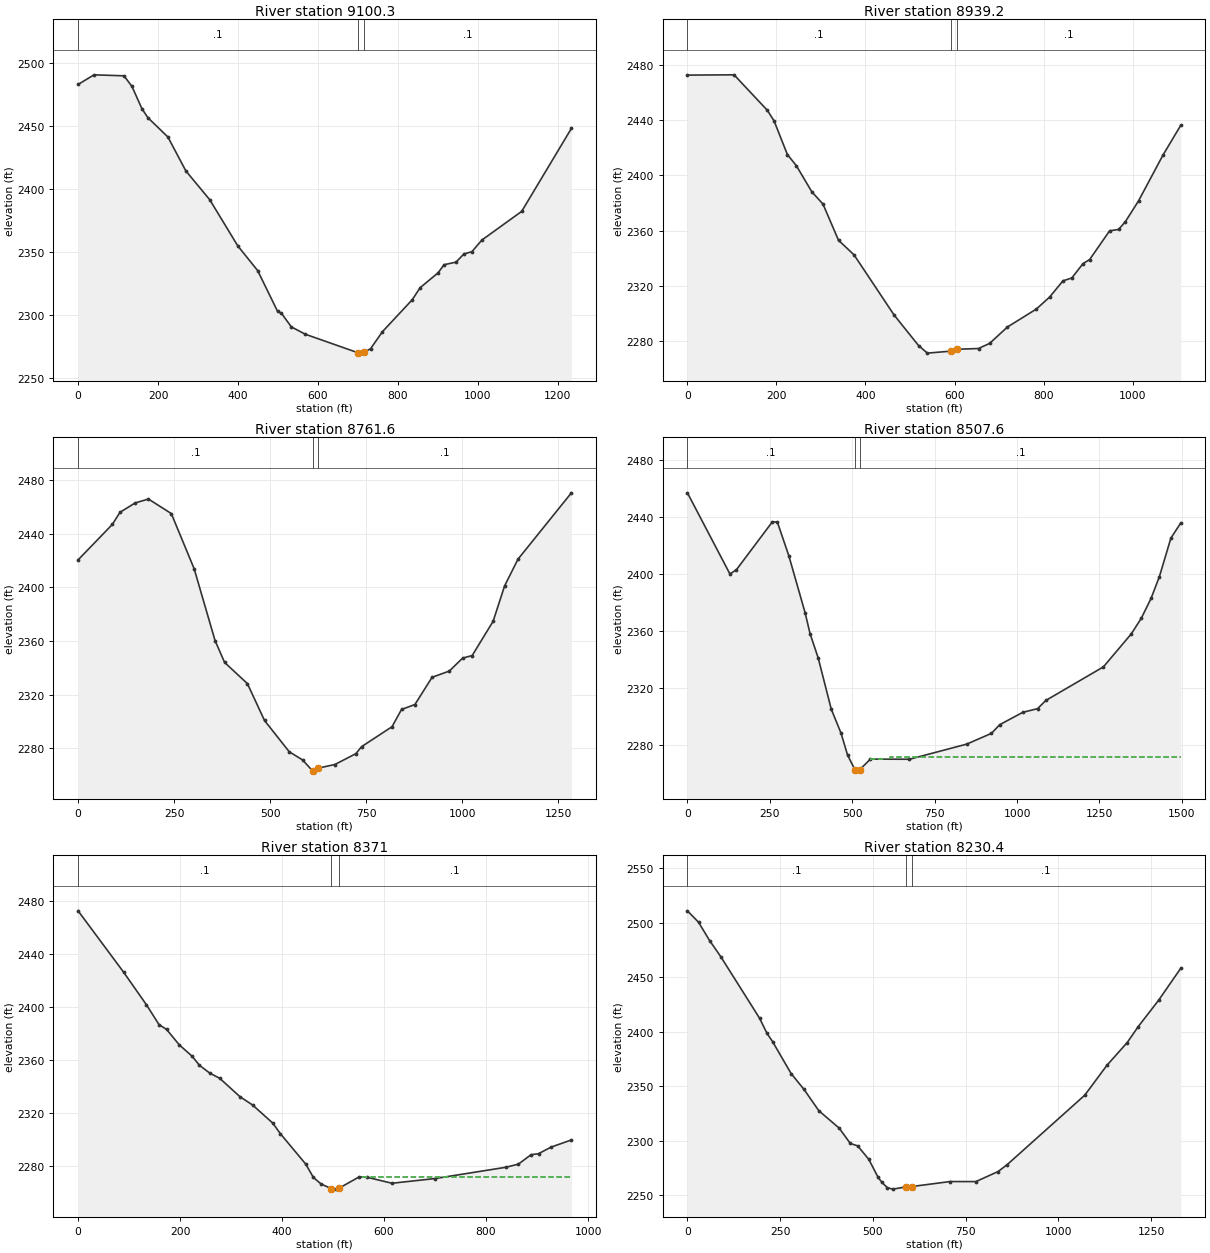
Type RM Length L Ch R = 1 ,9100.3  ,158.8,161.1,172.1
XS GIS Cut Line= 4
     1878335.356      190428.118      1878748.43      190591.712
     1879128.785      190563.083     1879500.961      190730.767
#Sta/Elev= 30
       0 2483.14    39.9  2490.8   114.8 2490.02   134.8 2481.56   159.7 2463.88
   174.7 2456.73   224.6 2441.42   269.6 2414.45   329.5 2391.48   399.4  2354.9
   449.2 2335.24   498.8 2302.97   508.7 2301.29   533.4 2290.53   568.1 2284.73
   700.7  2269.9   706.8 2269.68   715.7 2270.43   731.6 2273.21   761.3 2286.74
   835.7 2312.07   855.6  2321.7   900.4 2333.47   915.3 2339.92   945.2 2341.98
   965.1 2348.49     985 2350.28  1009.9  2359.5  1109.5 2382.31  1233.9 2448.24
#Mann= 3 , 0 , 0
       0      .1       0   700.7    .045       0   715.7      .1       0
Bank Sta=700.7,715.7
XS Rating Curve= 0 ,0
Exp/Cntr=0.3,0.1

Type RM Length L Ch R = 1 ,8939.2  ,176.1,177.6,178.9
XS GIS Cut Line= 2
     1878381.401       190521.95     1879440.701      190847.464
#Sta/Elev= 30
       0 2472.66   104.8 2472.86   179.7  2447.1   194.7 2439.45   224.6 2415.08
   244.6 2407.08   279.5 2388.09   304.5 2379.21   339.4    2353   374.4 2342.37
   464.2 2298.85   519.2  2276.7   539.1 2271.19   591.7 2272.64   606.7    2274
   653.9 2274.54   678.9 2278.25   718.8  2290.1   783.7  2303.1   813.7 2311.84
   843.6 2323.56   863.6 2325.68   888.6 2336.04   903.5 2338.98   948.4 2359.82
   968.4 2360.81   983.4 2366.24  1013.3 2381.47  1068.2 2414.66  1108.2 2436.28
#Mann= 3 , 0 , 0
       0      .1       0   591.7    .045       0   606.7      .1       0
Bank Sta=591.7,606.7
XS Rating Curve= 0 ,0
Exp/Cntr=0.3,0.1

Type RM Length L Ch R = 1 ,8761.6  ,248.2,254,259.9
XS GIS Cut Line= 4
     1878338.501      190719.035     1878727.981      190792.114
     1879104.246      190931.169     1879590.937      190947.528
#Sta/Elev= 30
       0 2420.38    89.2 2446.85     109 2455.84   148.6 2462.87   183.3 2465.76
   242.7 2454.93   302.2 2413.77   356.6 2360.24   381.4 2343.95   440.8 2328.12
   485.4 2300.63   549.8  2277.3   584.5 2271.22   610.8 2262.96   614.2 2262.87
   625.8 2265.14   668.6 2267.81   723.1 2275.86     738  2281.1   817.3 2295.99
   842.1 2308.85   876.9 2312.53   921.6 2332.83   966.4 2337.48  1001.2 2347.16
    1026 2349.06  1080.6 2374.64  1110.5 2401.05  1145.2 2420.88  1284.4  2470.4
#Mann= 3 , 0 , 0
       0      .1       0   610.8    .045       0   625.8      .1       0
Bank Sta=610.8,625.8
XS Rating Curve= 0 ,0
Exp/Cntr=0.3,0.1

Type RM Length L Ch R = 1 ,8507.6  ,140,136.6,133.2
XS GIS Cut Line= 4
     1878274.009      190865.731     1878646.184      190951.618
     1878965.192      191168.379     1879689.093      191254.266
#Sta/Elev= 30
       0 2456.77     129 2399.92   148.8 2402.94   257.9 2436.52   272.8  2436.3
   307.6 2412.75   357.2 2372.64     372 2358.19   396.8 2341.08   436.4 2305.24
     466 2288.47   485.8 2273.15   508.4 2262.71   515.5 2261.85   523.4 2262.98
     555 2270.27   673.7 2270.17   847.5 2280.78   922.4 2288.32   947.4 2294.36
  1017.3 2303.03  1062.2  2305.6  1087.2 2311.34    1262 2334.87  1346.8 2358.05
  1376.8 2368.87  1406.7 2382.92  1431.7    2398  1466.7 2425.05  1496.6 2435.65
#Mann= 3 , 0 , 0
       0      .1       0   508.4    .045       0   523.4      .1       0
#XS Ineff= 2 ,-1
  554.94  604.38 2270.34  615.88  1496.6 2271.84
Permanent Ineff=
       F       F
Bank Sta=508.4,523.4
XS Rating Curve= 0 ,0
Exp/Cntr=0.3,0.1

Type RM Length L Ch R = 1 ,8371    ,132.4,140.6,145.5
XS GIS Cut Line= 4
      1878260.42      190945.705     1878622.508      191107.782
     1878770.791      191178.475     1879134.603      191359.519
#Sta/Elev= 30
       0 2472.83    89.3 2426.45   133.9 2401.89   158.7 2386.84   173.6 2383.15
   198.4 2371.54   223.2 2363.06     238 2356.07   257.9 2350.24   277.7 2346.23
   317.4 2332.34   342.2 2326.05   381.8 2312.35   396.7 2304.35   446.5 2281.32
   461.4  2271.3   476.4 2266.36   496.2  2262.9   506.2 2262.45   511.2 2263.04
     551 2271.67   565.9 2271.51   615.5 2266.89   699.7 2270.44   838.5 2278.95
   863.3 2281.31   888.1 2288.43   902.9 2289.25   927.7 2294.24   967.4 2299.63
#Mann= 3 , 0 , 0
       0      .1       0   496.2    .045       0   511.2      .1       0
#XS Ineff= 2 , 0
                          557.05         2271.79
Permanent Ineff=
       F       F
Bank Sta=496.2,511.2
XS Rating Curve= 0 ,0
Exp/Cntr=0.3,0.1

Type RM Length L Ch R = 1 ,8230.4  ,238.8,234.8,235.6
XS GIS Cut Line= 4
     1878196.302      190976.157     1878543.938      191201.098
     1878831.308      191350.007      1879271.93      191745.047
#Sta/Elev= 30
       0 2511.09    29.9 2500.68    59.9 2483.74    89.8 2469.04   194.6 2412.35
   214.5 2398.49   229.5 2390.96   279.4 2361.63   314.3 2346.98   354.2 2327.44
   409.1 2311.44     439 2297.39   458.9 2295.15   488.8  2282.8   513.6 2266.42
   523.6 2261.87   538.6 2256.76   553.5 2255.42   589.5 2257.49   604.5 2257.79
   707.8 2262.38   777.5 2262.36   837.2 2271.57     862 2277.99  1070.9 2341.75
  1130.6  2369.2  1185.3 2390.11  1215.1 2404.82  1269.8 2428.91  1329.5 2458.31
#Mann= 3 , 0 , 0
       0      .1       0   589.5    .045       0   604.5      .1       0
Bank Sta=589.5,604.5
XS Rating Curve= 0 ,0
Exp/Cntr=0.3,0.1

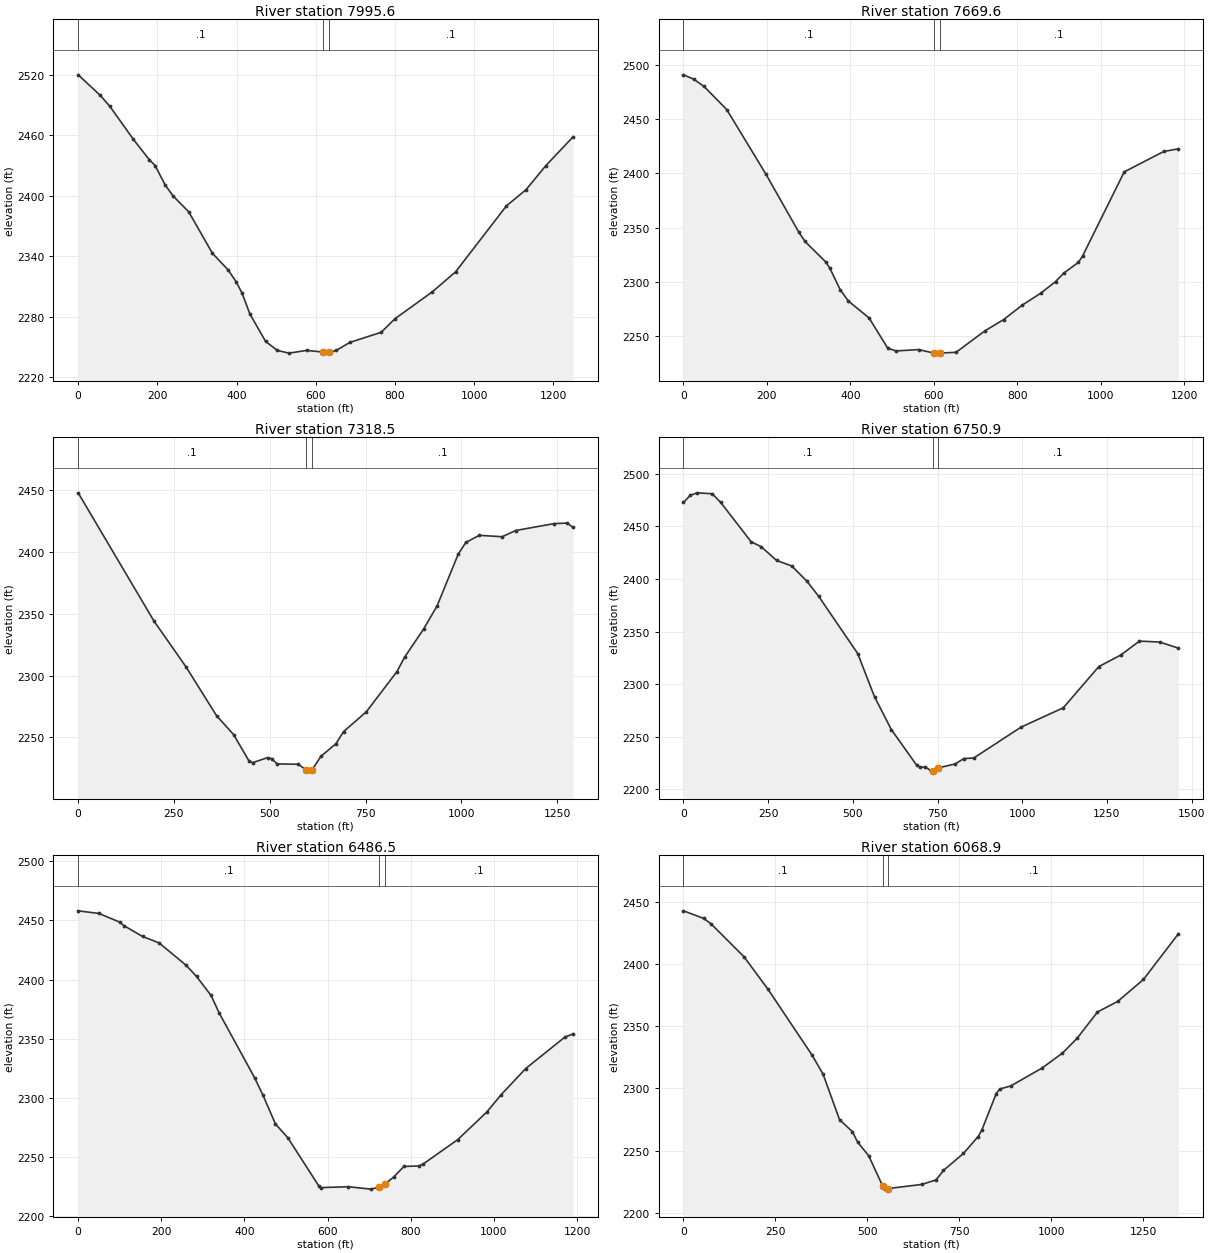
Type RM Length L Ch R = 1 ,7995.6  ,317.3,326,343.6
XS GIS Cut Line= 4
     1878163.583      191123.391      1878490.77      191368.781
     1878813.868      191630.531     1879181.953      191843.203
#Sta/Elev= 30
       0 2519.85    54.9 2499.86    79.8 2488.73   139.6 2455.86   179.6 2435.75
   194.5  2429.9   219.4 2410.92   239.4 2399.93   279.3 2384.05   339.2 2342.94
   379.1 2326.36     399 2314.79   413.9 2303.53   433.7 2282.87   473.3  2255.7
     503 2246.71   532.7 2244.05   577.3 2246.77     619 2245.06     634 2244.69
   651.5 2246.67   686.2 2254.67   765.4 2264.69     800 2278.09     894 2304.62
   953.3 2324.63  1081.8 2390.04  1131.3 2406.08  1180.7 2429.64  1249.9  2458.4
#Mann= 3 , 0 , 0
       0      .1       0     619    .045       0     634      .1       0
Bank Sta=619,634
XS Rating Curve= 0 ,0
Exp/Cntr=0.3,0.1

Type RM Length L Ch R = 1 ,7669.6  ,343.1,351.1,359
XS GIS Cut Line= 4
     1878057.044      191217.004     1878274.009      191466.938
     1878529.687      191874.364     1878817.958      192113.132
#Sta/Elev= 30
       0 2490.79    24.7 2486.76    49.4 2480.04   103.7  2458.8   197.6 2399.33
   276.6 2345.77   291.4  2337.3   340.9 2318.48   350.8 2312.75   375.6 2292.89
   395.4 2282.38     445 2266.79   489.6 2239.02   509.5 2236.45     564 2237.73
   599.8 2234.47   603.7 2234.44   614.8 2234.55   653.3 2235.17   722.7 2254.97
   767.4 2265.34     812 2278.64   856.9 2289.78   891.8 2300.29   911.8 2308.22
   946.7    2318   956.7  2323.9  1056.5 2401.39  1151.4  2420.2  1186.3 2422.63
#Mann= 3 , 0 , 0
       0      .1       0   599.8    .045       0   614.8      .1       0
Bank Sta=599.8,614.8
XS Rating Curve= 0 ,0
Exp/Cntr=0.3,0.1

Type RM Length L Ch R = 1 ,7318.5  ,570.4,567.6,566.4
XS GIS Cut Line= 4
     1877927.047      191267.116     1878053.158      191589.633
     1878139.044      191965.898      1878507.13      192387.151
#Sta/Elev= 30
       0 2447.75   197.9 2344.07     282 2306.82   361.1 2267.61   405.7 2252.32
   445.3 2231.31   455.2 2229.59   494.7  2233.7   504.6  2232.9   519.5 2228.59
   573.9 2228.33   595.1 2223.85   603.6 2222.76   610.1 2223.55   633.3 2234.64
   672.9 2244.97   692.7  2254.7   752.2 2270.76   832.1 2303.29   852.1 2314.95
   902.1 2337.86     937 2356.51     992 2398.24  1011.9 2407.67  1046.9  2413.4
  1106.8 2412.26  1141.8 2417.28  1241.7 2422.84  1276.7  2423.3  1291.6 2419.76
#Mann= 3 , 0 , 0
       0      .1       0   595.1    .045       0   610.1      .1       0
Bank Sta=595.1,610.1
XS Rating Curve= 0 ,0
Exp/Cntr=0.3,0.1

Type RM Length L Ch R = 1 ,6750.9  ,252,264.4,288.2
XS GIS Cut Line= 4
     1877844.129      191119.034     1877699.364      191612.604
     1877654.475      192097.375      1877852.61      192512.006
#Sta/Elev= 30
       0 2472.58      20 2479.34      40 2481.76    84.9 2480.89   109.9 2472.64
   199.8 2435.25   229.7 2430.58   274.7 2417.54   319.6 2412.32   364.6 2397.76
   399.5  2383.3   514.4 2329.08     564 2287.98   613.7 2256.82   688.2 2223.16
   698.2    2221   713.1 2221.47   732.9 2217.43   736.6 2217.78   751.6  2220.5
   802.5  2224.3   827.3 2229.32   857.1 2229.93   996.2 2259.19  1121.1 2277.58
    1226 2316.72  1290.9 2327.71  1345.9 2340.92  1405.8 2340.05  1460.8 2334.24
#Mann= 3 , 0 , 0
       0      .1       0   736.6    .045       0   751.6      .1       0
Bank Sta=736.6,751.6
XS Rating Curve= 0 ,0
Exp/Cntr=0.3,0.1

Type RM Length L Ch R = 1 ,6486.5  ,414.1,417.6,420.9
XS GIS Cut Line= 4
     1877676.892      191201.098     1877590.604      191677.691
     1877440.395      192041.946     1877394.694      192350.343
#Sta/Elev= 30
       0 2458.17    49.9 2455.95    99.9  2448.6   109.8 2445.69   154.8 2436.46
   194.7    2431   259.6 2412.09   284.6 2402.66   319.6 2386.56   339.5 2371.48
   424.4 2316.87   444.4 2302.14   474.4 2277.82   504.3 2266.04   579.1 2225.11
   584.1 2223.91   648.9 2224.67   703.8 2222.63   723.7 2224.24   738.7 2227.17
   758.6 2232.86   783.6 2241.84   818.5 2242.21   828.5  2243.6     913 2264.59
   982.3 2287.75  1016.9 2302.41  1076.3 2324.71  1170.3 2351.26  1190.1 2354.03
#Mann= 3 , 0 , 0
       0      .1       0   723.7    .045       0   738.7      .1       0
Bank Sta=723.7,738.7
XS Rating Curve= 0 ,0
Exp/Cntr=0.3,0.1

Type RM Length L Ch R = 1 ,6068.9  ,432.1,408.1,384.2
XS GIS Cut Line= 4
     1877628.772      191187.025     1877374.244      191434.219
     1877120.674      191859.562     1877210.651      192346.253
#Sta/Elev= 30
       0 2442.89      55 2436.78      75  2432.4   164.9 2405.78   229.9  2379.7
   349.8 2326.65   379.6 2311.32   424.1 2274.86   458.8 2265.27   473.6 2256.61
   503.4 2245.83   541.9 2221.09   547.9 2218.96   556.9 2219.45     647 2222.73
   686.6 2226.38   706.4 2233.98   760.9 2247.67   800.5  2261.2   810.4 2266.16
     850 2295.88     860 2299.54     890 2302.05     975 2316.48    1030 2328.42
    1070  2340.4    1125 2361.46    1180    2370    1250 2387.64  1344.9  2424.4
#Mann= 3 , 0 , 0
       0      .1       0   541.9    .045       0   556.9      .1       0
Bank Sta=541.9,556.9
XS Rating Curve= 0 ,0
Exp/Cntr=0.3,0.1

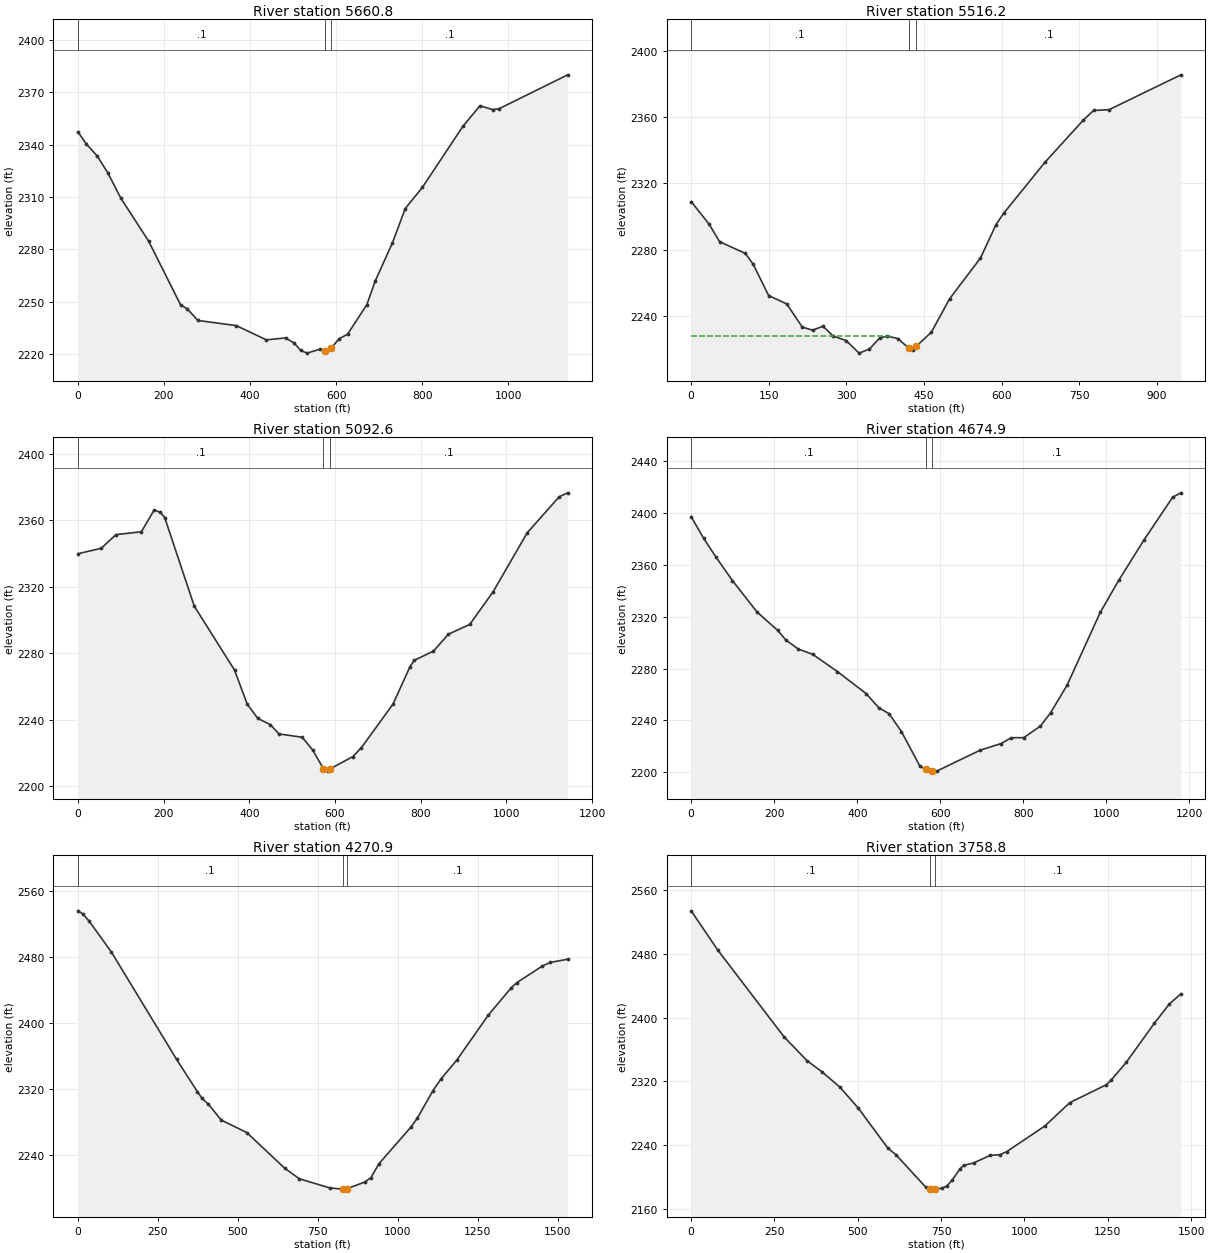
Type RM Length L Ch R = 1 ,5660.8  ,152.4,144.6,136.8
XS GIS Cut Line= 4
     1876670.749      191111.685     1876830.296      191471.027
     1876961.171      191716.418      1876981.62      192182.659
#Sta/Elev= 30
       0 2347.34    19.9 2340.32    44.8 2333.54    69.7 2323.79    99.5 2309.47
   164.2 2284.82   238.9 2248.12   253.8 2246.13   278.7 2239.36   368.3 2236.38
   437.9 2228.23   482.6 2229.36   502.4  2226.4   517.3  2222.3   532.2 2220.64
     562 2222.85   574.2 2221.81   589.2 2223.71   606.7 2228.82   626.6 2231.48
   671.3 2248.37   691.1 2262.09   730.9 2283.82   760.6 2303.41   800.4 2315.52
   894.7 2350.56   934.4 2362.29   964.2 2360.05   979.1 2360.64    1138 2379.99
#Mann= 3 , 0 , 0
       0      .1       0   574.2    .045       0   589.2      .1       0
Bank Sta=574.2,589.2
XS Rating Curve= 0 ,0
Exp/Cntr=0.3,0.1

Type RM Length L Ch R = 1 ,5516.2  ,412.9,423.6,435.8
XS GIS Cut Line= 3
     1876486.021      191421.111     1876925.789      191834.755
     1876965.279       192174.68
#Sta/Elev= 30
       0 2309.03    34.9  2295.3    54.9 2284.82   104.8 2277.71   119.8 2271.19
   149.7 2252.28   184.6 2247.27   214.6  2233.3   234.5 2231.42   254.5 2233.78
   274.4 2227.84   299.4 2225.12   324.3 2217.56   344.3 2220.03   364.2 2226.72
   379.2 2227.78   399.2 2226.35   419.8 2220.72   429.1 2219.68   434.8  2221.7
     464  2230.2     499 2250.28   558.8 2274.92   588.8 2295.13   603.7 2301.99
   683.1 2332.64   757.5 2358.19   777.3 2364.02   807.1 2364.46     946 2385.51
#Mann= 3 , 0 , 0
       0      .1       0   419.8    .045       0   434.8      .1       0
#XS Ineff= 2 , 0
          384.41 2227.97
Permanent Ineff=
       F       F
Bank Sta=419.8,434.8
XS Rating Curve= 0 ,0
Exp/Cntr=0.3,0.1

Type RM Length L Ch R = 1 ,5092.6  ,425.8,417.7,408
XS GIS Cut Line= 4
      1876361.59      191288.622     1876490.839       191667.34
     1876529.826      192015.381      1876728.05      192354.433
#Sta/Elev= 30
       0 2339.98    54.3 2343.24    88.9 2351.48   148.2 2353.21   177.8 2366.28
   192.7 2364.87   202.6 2361.72   271.7 2308.36   365.6 2269.88   395.2 2249.39
   419.9 2240.81   449.5    2237   469.2 2231.46   523.5 2229.47   548.1 2221.75
   572.9 2210.58   582.7 2209.07   587.9 2210.32   641.9 2217.85   661.6 2223.19
   735.6  2249.5   775.2 2272.02   785.2 2275.82   829.9 2281.31   864.7 2291.51
   914.4 2297.36   969.1 2317.07  1048.7  2352.6  1123.2 2374.24  1143.1 2376.64
#Mann= 3 , 0 , 0
       0      .1       0   572.9    .045       0   587.9      .1       0
Bank Sta=572.9,587.9
XS Rating Curve= 0 ,0
Exp/Cntr=0.3,0.1

Type RM Length L Ch R = 1 ,4674.9  ,402.2,404,403.4
XS GIS Cut Line= 4
     1875930.531      191438.309     1876094.125      191896.371
     1876269.988      192100.863     1876493.288      192460.541
#Sta/Elev= 30
       0 2397.38    29.8 2380.76    59.6 2366.27    99.3 2348.06   158.8  2323.7
   208.5 2309.54   228.3 2302.04   258.1 2295.12   292.8 2291.04   352.4  2277.7
   421.9 2260.63   451.7 2249.82   476.5 2245.26   506.4 2231.42   551.3 2204.46
     565 2202.51     580 2201.32   591.3 2200.87   696.2 2217.06   746.1 2222.13
     771 2226.65   800.9 2226.71   840.8 2235.54   865.7 2245.93   905.5 2267.36
   985.2 2323.46    1030 2348.36  1089.8 2379.02  1159.6 2412.39  1179.5 2415.77
#Mann= 3 , 0 , 0
       0      .1       0     565    .045       0     580      .1       0
Bank Sta=565,580
XS Rating Curve= 0 ,0
Exp/Cntr=0.3,0.1

Type RM Length L Ch R = 1 ,4270.9  ,537.5,512.1,507.1
XS GIS Cut Line= 4
     1875603.344      191605.992     1875787.387      192100.863
     1876135.023      192464.858     1876597.175      192657.081
#Sta/Elev= 30
       0 2535.64    14.9  2532.1    34.9 2523.32   104.6 2485.84   308.8 2355.67
   373.6 2316.69   388.5 2308.42   408.4 2301.37   448.3 2282.31     528 2267.18
   647.6 2223.68   692.4  2211.2   787.1 2200.17     827 2198.65   827.7 2198.66
   842.7 2199.35   896.8 2207.16   916.7  2212.7   941.6 2229.43  1041.2 2273.63
    1061 2284.22  1110.6 2317.97  1135.4 2331.97    1185 2354.93  1284.1 2409.61
  1353.4  2441.6  1373.3  2448.8  1452.6  2468.8  1477.3 2473.17  1531.8 2477.03
#Mann= 3 , 0 , 0
       0      .1       0   827.7    .045       0   842.7      .1       0
Bank Sta=827.7,842.7
XS Rating Curve= 0 ,0
Exp/Cntr=0.3,0.1

Type RM Length L Ch R = 1 ,3758.8  ,140,133.6,127.2
XS GIS Cut Line= 4
     1875276.157      191945.449     1875513.367      192329.894
     1875795.566      192599.823     1876359.964      192873.842
#Sta/Elev= 30
       0 2534.19    79.4 2485.16     278 2376.24   347.5 2345.98   392.2 2332.05
   446.8 2312.48   501.2 2286.52   590.2 2236.04   614.9 2227.62   703.8 2187.07
   716.5 2185.14   731.5 2184.57   733.5 2184.55   753.3 2185.73   768.1 2188.92
   782.9 2195.75   807.6 2210.43   817.5 2214.29   847.2 2217.34     897 2226.97
   926.9 2227.86   946.8 2231.65  1061.3 2263.84    1136 2293.14  1245.6 2315.67
  1260.5 2321.62  1305.3 2343.72    1390 2393.05  1434.8 2417.12  1469.6 2429.95
#Mann= 3 , 0 , 0
       0      .1       0   716.5    .045       0   731.5      .1       0
Bank Sta=716.5,731.5
XS Rating Curve= 0 ,0
Exp/Cntr=0.3,0.1

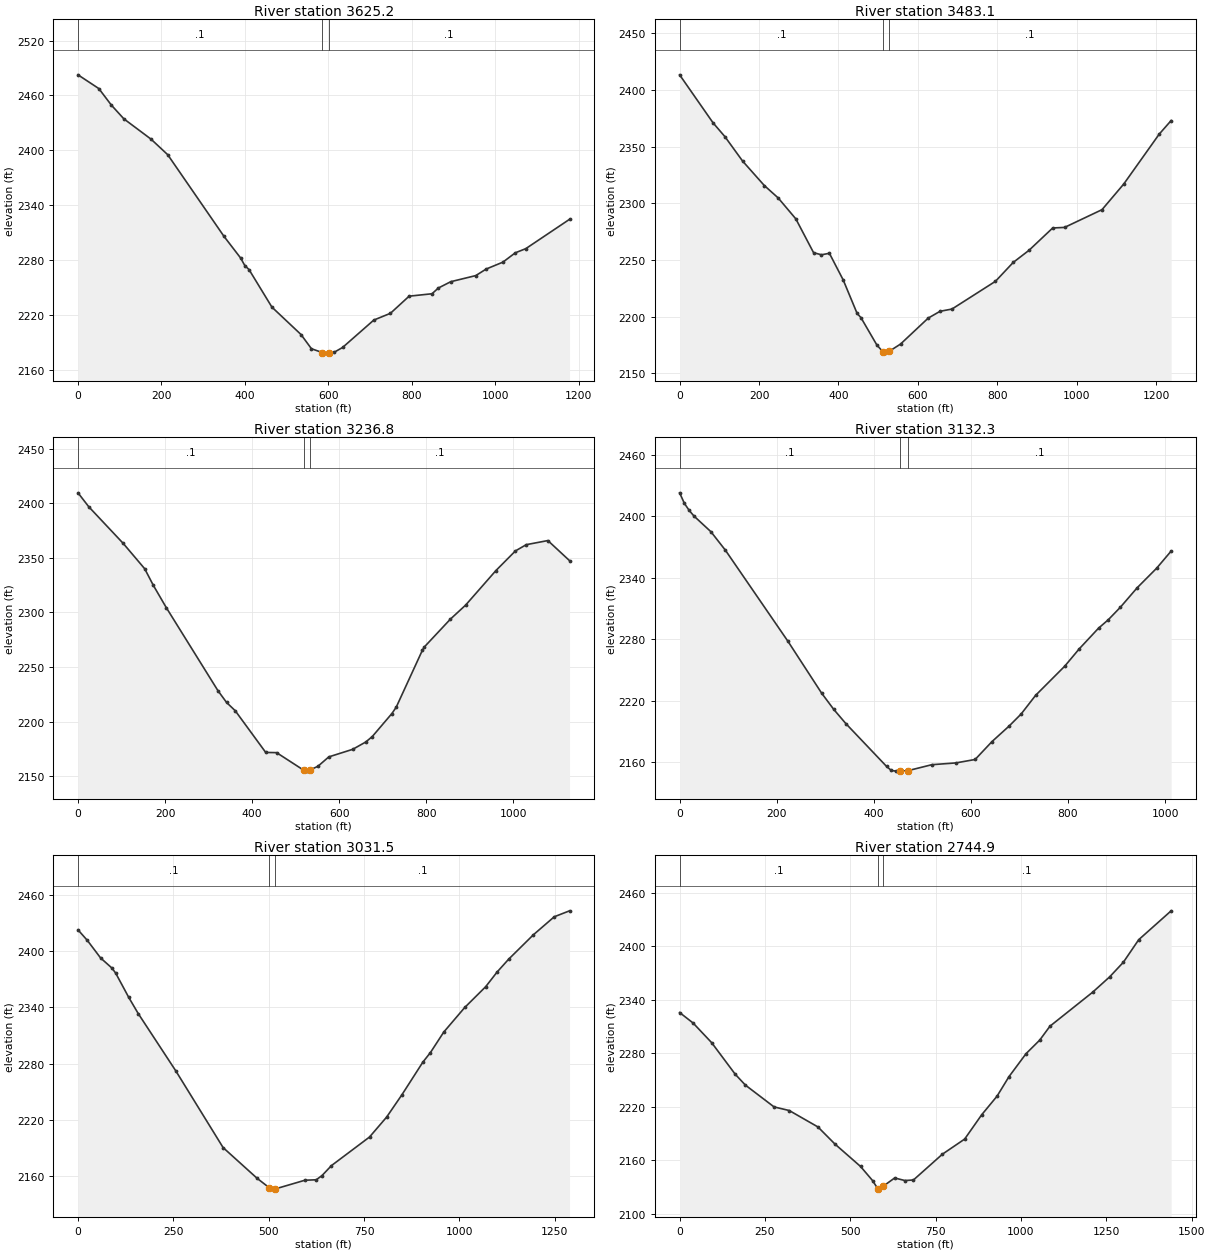
Type RM Length L Ch R = 1 ,3625.2  ,138.9,142.1,145.4
XS GIS Cut Line= 4
     1875217.312      192173.379     1875498.953      192511.348
      1875806.88      192740.415     1876118.562        192909.4
#Sta/Elev= 30
       0  2482.5      50 2467.46      80 2449.38     110 2434.36     175 2412.21
     215 2395.21     350 2305.88   389.9  2282.2   399.9 2273.97   409.9 2269.65
   464.9 2228.51   534.6 2198.58   559.6 2183.04     586 2178.83   599.4 2178.23
     601 2178.27   614.4 2179.24   634.3 2184.42   709.1 2214.37     749 2221.77
   793.8  2240.5   848.7 2243.14   863.7 2249.37   893.6 2256.33   953.6 2263.01
   978.5 2270.17  1018.5 2277.68  1048.4 2287.93  1073.4 2292.44  1178.3 2324.52
#Mann= 3 , 0 , 0
       0      .1       0     586    .045       0     601      .1       0
Bank Sta=586,601
XS Rating Curve= 0 ,0
Exp/Cntr=0.3,0.1

Type RM Length L Ch R = 1 ,3483.1  ,246.5,246.3,252.5
XS GIS Cut Line= 4
     1875161.641      192293.085     1875349.774      192554.835
     1875726.039      192849.303     1876122.753      193033.346
#Sta/Elev= 30
       0 2413.48    84.3 2371.03   114.1 2358.86   158.7 2337.26   213.2 2315.72
     248 2304.79   292.6 2286.26   337.3 2256.36   357.2 2254.53   377.1 2255.85
   411.9 2232.27   446.8 2202.81   456.7 2198.92   496.5  2174.9     513 2168.37
   516.4 2167.66     528 2169.32   556.3 2175.69   625.9  2198.6   655.8 2204.62
   685.7 2206.59   795.2 2231.09   839.9 2247.78   879.6 2258.46   939.3 2278.21
   969.1  2278.7  1063.5 2294.39  1118.2 2317.04  1207.6 2361.16  1237.5  2373.1
#Mann= 3 , 0 , 0
       0      .1       0     513    .045       0     528      .1       0
Bank Sta=513,528
XS Rating Curve= 0 ,0
Exp/Cntr=0.3,0.1

Type RM Length L Ch R = 1 ,3236.8  ,96.1,104.5,112.1
XS GIS Cut Line= 4
     1875012.517      192501.943     1875222.989      192751.147
     1875566.535      193033.346     1875914.579      193117.369
#Sta/Elev= 30
       0 2409.49    24.7 2396.76   103.8 2363.23   153.2    2340     173 2324.82
   202.6 2304.53   321.2 2228.54   341.2 2217.63   361.2 2210.02   431.1 2171.89
   456.1  2171.7   518.3 2155.64     526 2154.78   533.3 2155.93     551 2159.21
     576 2167.82   630.9 2174.74   660.9 2181.45   675.9 2186.46   720.8 2207.44
   730.8 2213.29   790.7 2265.23   795.6 2268.51   855.3 2293.92   890.1 2306.69
   959.8 2338.36  1004.5  2356.3  1029.4 2362.04  1079.1  2365.8  1128.8 2347.42
#Mann= 3 , 0 , 0
       0      .1       0   518.3    .045       0   533.3      .1       0
Bank Sta=518.3,533.3
XS Rating Curve= 0 ,0
Exp/Cntr=0.3,0.1

Type RM Length L Ch R = 1 ,3132.3  ,105.4,100.8,96.3
XS GIS Cut Line= 4
     1874982.826      192570.377     1875230.212      192834.908
     1875337.984      193011.263     1875720.085      193236.604
#Sta/Elev= 30
       0 2423.06     9.9  2412.7    19.8 2405.83    29.8 2400.28    64.5 2385.07
    94.3 2367.02   223.3 2277.93   292.7 2227.28   317.5 2211.51   342.3 2197.71
   426.2 2155.86     436 2151.87   445.8  2151.2   454.9 2151.24   469.9  2151.6
   519.6 2157.49   568.9 2159.21   608.7 2162.57   643.6 2180.11   678.5 2195.12
   703.4 2206.95   733.3 2225.21   793.2 2253.66   823.1 2270.59   862.9 2290.82
   882.9 2299.01   907.8 2311.22   942.7  2330.4   982.6 2349.41  1012.5 2366.14
#Mann= 3 , 0 , 0
       0      .1       0   454.9    .045       0   469.9      .1       0
Bank Sta=454.9,469.9
XS Rating Curve= 0 ,0
Exp/Cntr=0.3,0.1

Type RM Length L Ch R = 1 ,3031.5  ,293.5,286.6,279.7
XS GIS Cut Line= 4
      1874944.88      192575.284     1875092.114      192865.663
     1875419.301      193201.029     1875893.722      193340.084
#Sta/Elev= 30
       0 2422.54    24.7  2411.2    59.2  2392.6    88.8 2381.86    98.7 2376.48
   133.2 2350.44   157.8 2333.36   256.5 2272.16   380.4 2190.48   470.1 2157.55
   501.5 2147.68     515 2146.21   516.5 2146.35   594.7 2155.68   624.6 2156.18
   639.6 2160.64   664.5 2171.31   764.2 2201.73   809.1    2223     849 2246.69
     904 2281.53   923.9 2291.76   958.9 2313.63  1013.8 2339.78  1068.8 2361.98
  1098.7  2377.6  1128.7 2391.16  1193.6 2417.21  1248.5 2436.47  1288.5  2442.8
#Mann= 3 , 0 , 0
       0      .1       0   501.5    .045       0   516.5      .1       0
Bank Sta=501.5,516.5
XS Rating Curve= 0 ,0
Exp/Cntr=0.3,0.1

Type RM Length L Ch R = 1 ,2744.9  ,342.3,338.5,334.6
XS GIS Cut Line= 4
     1874767.437      192761.267     1874912.161      193139.682
     1875263.887      193340.084     1875873.273      193499.588
#Sta/Elev= 30
       0  2325.7    39.5 2313.92    93.9 2291.86     163  2256.4   192.7 2244.24
   276.7 2219.76   321.2 2215.71   405.2 2197.29   455.1 2178.06   530.1 2152.91
   565.1 2137.16   580.8 2127.82   585.1  2127.5   595.8  2130.6     630 2140.02
     660 2137.14     685 2137.76     770 2166.76     835 2183.66     885 2210.99
   929.9 2231.82   964.9 2253.74  1014.9 2279.54  1054.9 2294.73  1084.9 2310.34
  1209.9 2348.47  1259.9 2365.75  1299.9 2382.09  1344.9 2407.41  1439.9 2439.82
#Mann= 3 , 0 , 0
       0      .1       0   580.8    .045       0   595.8      .1       0
Bank Sta=580.8,595.8
XS Rating Curve= 0 ,0
Exp/Cntr=0.3,0.1