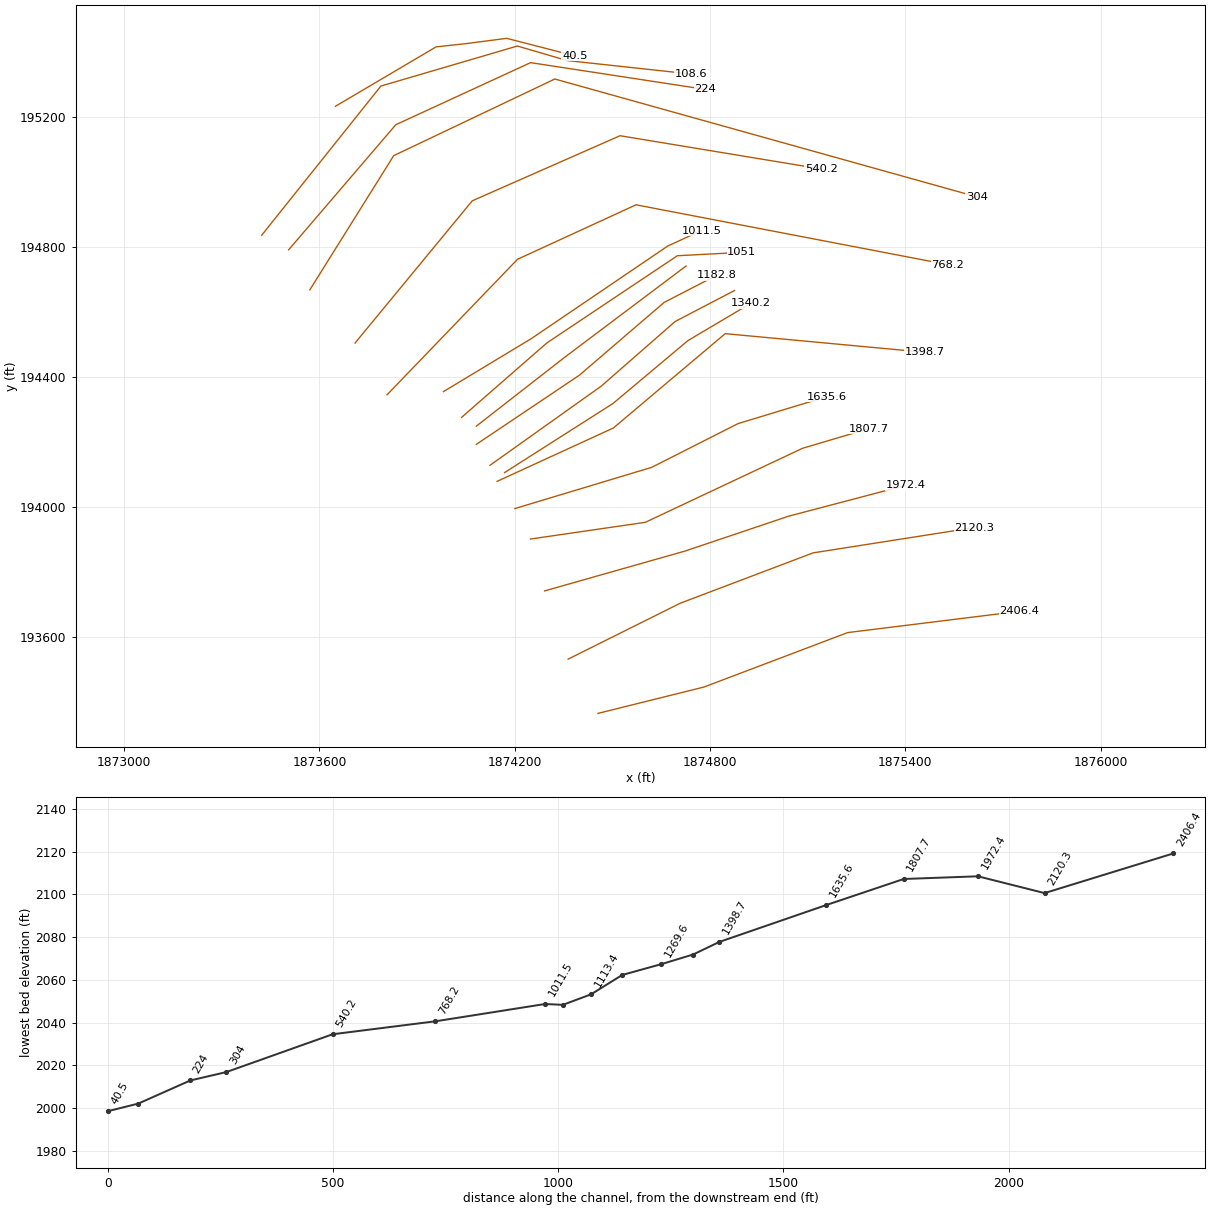
HEC-RAS study MilamFk2.prj: MilamFk2

--- MilamFk2.g01 (geometry) --- (continued)

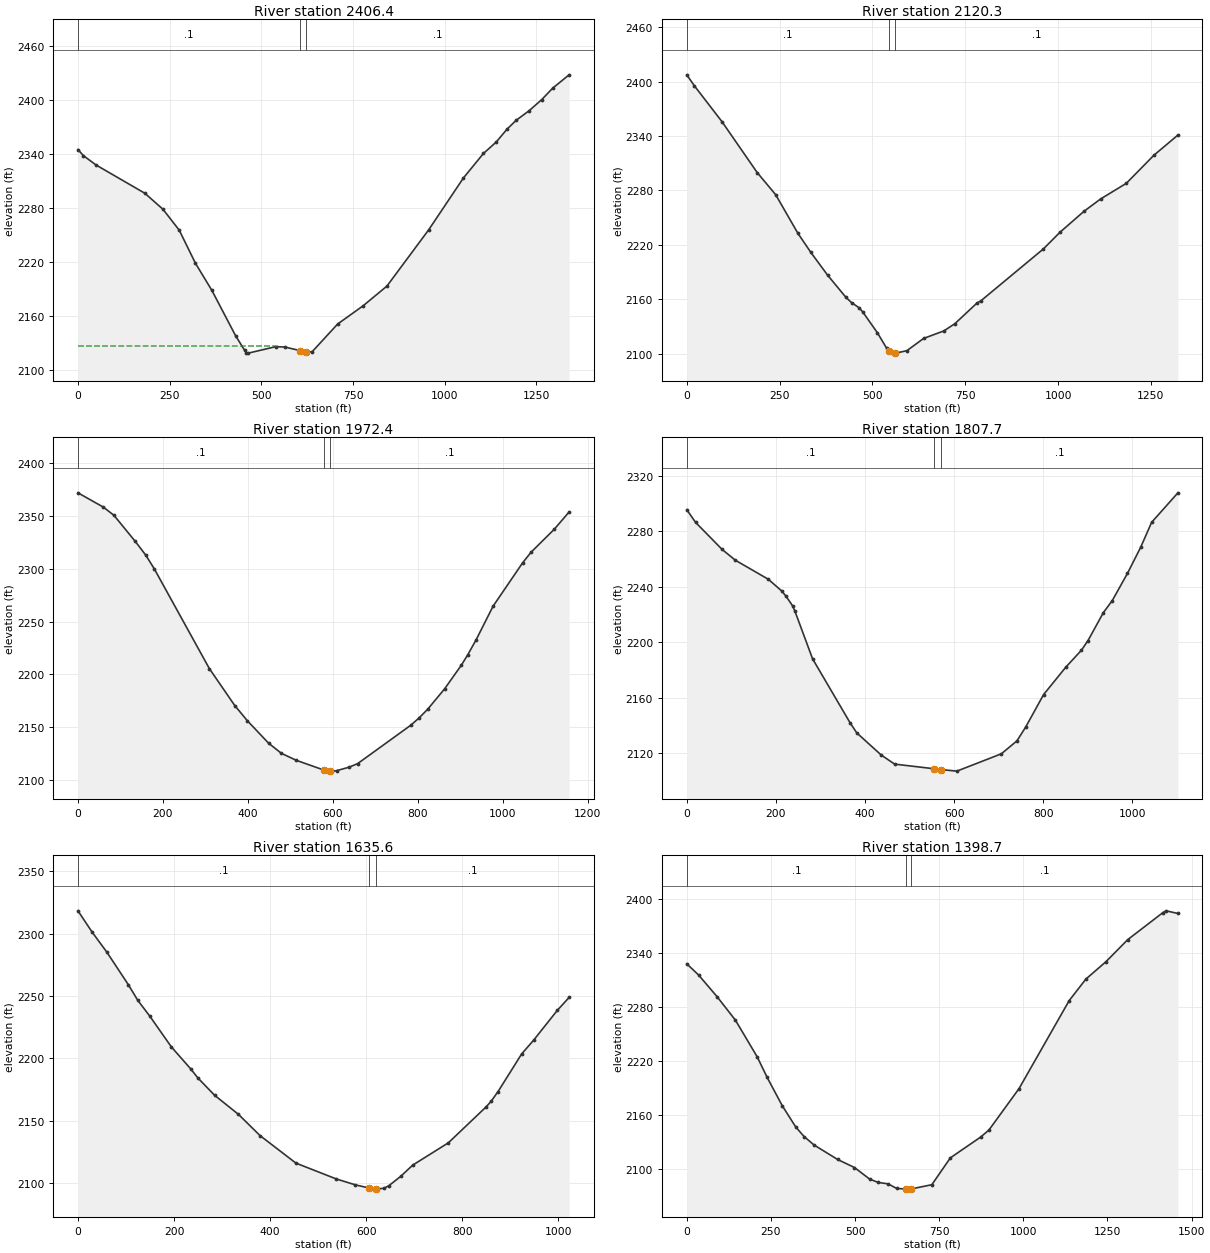
Type RM Length L Ch R = 1 ,2406.4  ,290.3,286.1,286.4
XS GIS Cut Line= 4
     1874455.916      193365.379     1874781.286       193446.42
     1875222.989      193614.103     1875750.578      193679.541
#Sta/Elev= 30
       0  2345.1    14.8 2338.38    49.3    2328   182.4 2296.64   231.8 2278.87
   276.1 2255.69   320.5 2218.86   365.2 2188.82   429.8 2138.57   454.7 2122.14
   459.6 2119.55   464.6 2119.19   539.2 2126.37   564.1 2125.96   606.4 2121.95
   621.4 2120.31   638.7 2120.75   708.3 2151.51   777.9 2171.78   842.6  2193.6
   956.8 2256.21  1051.2 2313.58  1105.9 2340.83  1140.7 2353.47  1170.5 2367.91
  1195.3 2377.67  1230.1 2388.13  1264.9  2400.6  1294.7 2413.26  1339.4 2428.07
#Mann= 3 , 0 , 0
       0      .1       0   606.4    .045       0   621.4      .1       0
#XS Ineff= 2 , 0
          546.86 2126.78
Permanent Ineff=
       F       F
Bank Sta=606.4,621.4
XS Rating Curve= 0 ,0
Exp/Cntr=0.3,0.1

Type RM Length L Ch R = 1 ,2120.3  ,148.8,147.9,147
XS GIS Cut Line= 4
     1874364.123      193532.307     1874707.669       193704.08
     1875116.653      193859.494     1875611.524      193937.201
#Sta/Elev= 30
       0 2407.44      20 2395.57    94.8 2355.79   189.6 2299.71   239.4 2275.28
   299.3 2232.68   334.2 2211.62   379.1 2186.64   428.8 2162.01   443.8 2156.28
   463.6 2150.74   473.6 2146.21   513.4 2123.02   538.2 2106.02   545.8 2102.49
   560.8 2100.66   563.1 2100.62   592.9 2103.36   637.7  2116.8   692.4 2125.13
   722.2 2133.14   781.8 2155.98   791.8 2158.21   960.5 2215.56  1005.1  2233.9
  1069.6 2256.94  1114.2 2270.52  1183.7 2287.82  1258.1 2318.83  1322.6 2341.03
#Mann= 3 , 0 , 0
       0      .1       0   545.8    .045       0   560.8      .1       0
Bank Sta=545.8,560.8
XS Rating Curve= 0 ,0
Exp/Cntr=0.3,0.1

Type RM Length L Ch R = 1 ,1972.4  ,157,164.7,174.5
XS GIS Cut Line= 4
     1874291.824      193742.349     1874723.698      193865.175
     1875040.669      193972.153     1875401.224      194067.244
#Sta/Elev= 30
       0 2371.82    59.9 2358.26    84.8 2350.52   134.7 2325.95   159.6 2312.88
   179.6 2299.96   309.3 2205.56   369.2 2170.54   399.1 2156.06     449 2134.87
     479 2125.33   513.9 2118.75   578.9  2109.5   593.9 2108.55   598.8 2108.48
   608.8  2108.9   638.7 2112.23   658.7 2115.62   783.5 2151.87   803.4 2158.88
   823.3 2166.98   863.1 2186.22   902.9 2208.83   917.8 2218.56   937.7 2232.88
   977.4 2264.53    1047 2305.59  1066.9 2315.63  1121.6 2337.38  1156.4 2353.68
#Mann= 3 , 0 , 0
       0      .1       0   578.9    .045       0   593.9      .1       0
Bank Sta=578.9,593.9
XS Rating Curve= 0 ,0
Exp/Cntr=0.3,0.1

Type RM Length L Ch R = 1 ,1807.7  ,176.8,172.1,165.1
XS GIS Cut Line= 4
     1874248.603      193902.122     1874601.333       193953.56
     1875084.275      194181.443     1875286.924      194241.606
#Sta/Elev= 30
       0 2295.37    19.8 2286.24    79.2 2266.81   108.9 2259.03   183.2 2245.26
   212.9  2236.9   222.8 2233.05   237.6 2226.08   242.6 2222.36   282.2 2188.08
   366.4    2142   381.4 2134.73   436.3  2118.8   466.3 2112.27   555.3 2108.91
   570.3 2108.34     606 2107.22   705.8 2119.69   740.8 2129.01   760.7 2139.12
   800.6 2162.33   850.5 2182.09   885.5 2194.26   900.3 2201.24   934.7 2221.34
   954.4 2229.83   988.8 2249.59  1018.3 2268.28  1042.9 2286.27  1101.9 2307.53
#Mann= 3 , 0 , 0
       0      .1       0   555.3    .045       0   570.3      .1       0
Bank Sta=555.3,570.3
XS Rating Curve= 0 ,0
Exp/Cntr=0.3,0.1

Type RM Length L Ch R = 1 ,1635.6  ,231.6,237,242.3
XS GIS Cut Line= 4
     1874200.695      193995.926     1874620.682      194122.714
     1874886.146      194257.427     1875159.533      194340.632
#Sta/Elev= 30
       0 2318.38    29.9 2301.05    59.8  2285.4   104.7 2259.18   124.6 2246.48
   149.6  2233.8   194.4 2209.15   234.3 2191.69   249.3 2184.37   284.2 2170.41
     334 2155.04   378.9    2138   453.6 2115.91   537.9 2103.15   577.6 2098.42
   606.3 2095.89   621.3 2095.05   622.3 2095.02   637.2 2095.78   647.1 2097.76
   671.9 2105.32   696.7 2114.28   770.9 2132.18   849.7 2161.09   859.6 2165.35
   874.4 2173.34   923.6  2203.6   948.3  2214.5   997.5  2238.4  1022.2 2248.85
#Mann= 3 , 0 , 0
       0      .1       0   606.3    .045       0   621.3      .1       0
Bank Sta=606.3,621.3
XS Rating Curve= 0 ,0
Exp/Cntr=0.3,0.1

Type RM Length L Ch R = 1 ,1398.7  ,58.6,58.5,58.4
XS GIS Cut Line= 4
     1874145.904      194079.636     1874503.177      194243.938
     1874846.723      194534.317     1875460.199      194477.059
#Sta/Elev= 30
       0 2327.75    34.8 2315.47    89.6 2291.48   144.4 2265.32   209.1 2224.62
   238.9 2201.64   283.7 2170.29   323.6 2146.82   348.4 2136.17   378.3 2126.72
   448.2 2110.68   498.2 2101.78   543.2 2088.95   568.2 2085.27   598.2 2083.61
   623.2 2078.65   651.4 2077.79   666.4 2077.95   728.1 2082.71   783.1 2112.48
   872.9 2135.49   897.7 2143.34   987.2 2189.33  1136.2    2287  1185.9 2310.86
  1245.6 2330.17  1310.1 2354.59  1414.5 2384.55  1424.4 2386.56  1459.2 2383.63
#Mann= 3 , 0 , 0
       0      .1       0   651.4    .045       0   666.4      .1       0
Bank Sta=651.4,666.4
XS Rating Curve= 0 ,0
Exp/Cntr=0.3,0.1

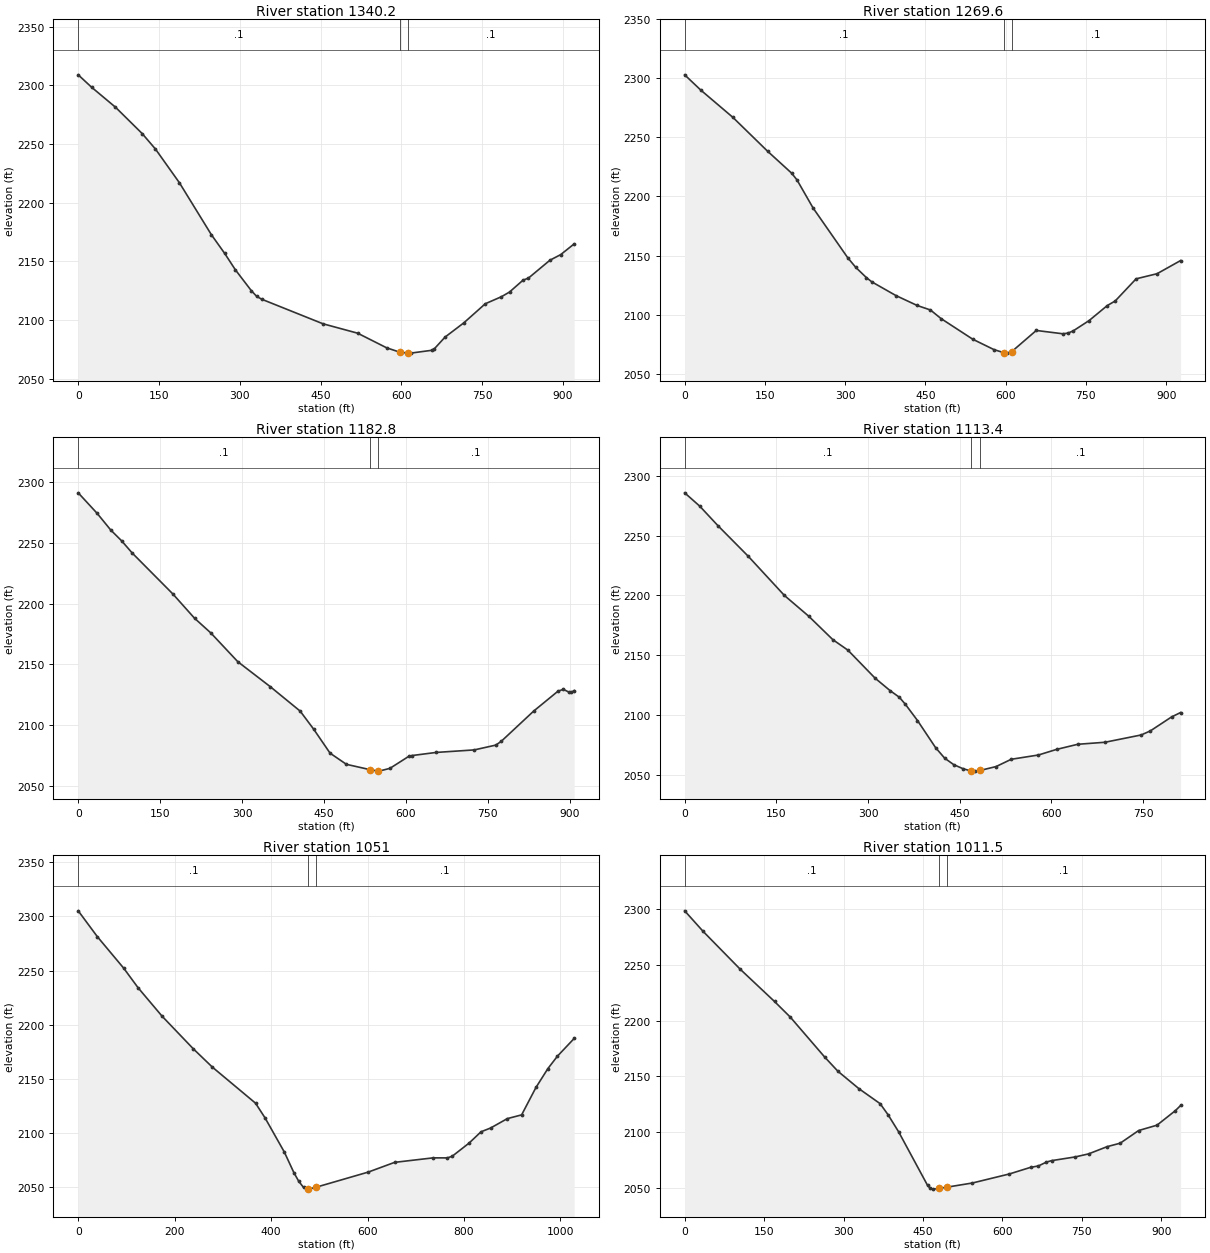
Type RM Length L Ch R = 1 ,1340.2  ,71.5,70.6,70.9
XS GIS Cut Line= 4
     1874169.018      194106.725     1874502.387      194319.633
     1874732.104      194512.931     1874925.402       194627.79
#Sta/Elev= 30
       0 2309.09    24.7 2298.57    69.2 2281.48   118.7 2259.04   143.4 2245.82
   187.9 2217.07   247.2  2172.8     272 2156.81   291.7 2142.92   321.4 2125.09
   331.3 2120.23   341.2 2117.71   454.6 2096.85   518.6 2088.89   572.7 2076.38
   597.1 2072.67   612.1 2071.89     617 2071.88   656.4  2074.3   661.3 2075.69
     681 2085.56   715.8 2097.69   755.7 2113.98   785.7 2119.98   800.7 2123.98
   825.7 2134.07   835.7 2135.82   875.7  2151.1   895.6 2155.84   920.6 2164.98
#Mann= 3 , 0 , 0
       0      .1       0   597.1    .045       0   612.1      .1       0
Bank Sta=597.1,612.1
XS Rating Curve= 0 ,0
Exp/Cntr=0.3,0.1

Type RM Length L Ch R = 1 ,1269.6  ,88.7,86.7,83.7
XS GIS Cut Line= 4
     1874124.195      194129.137     1874465.969       194372.86
     1874692.884      194571.761     1874874.977       194667.01
#Sta/Elev= 30
       0 2302.96      30 2290.08      90 2266.99   154.9 2238.32   199.9 2219.73
   209.9 2214.02   239.9 2190.32   304.8  2148.1   319.8 2139.96   339.8 2131.24
   349.8  2127.7   394.8 2116.12   434.6  2107.7   459.4 2103.89   479.1 2096.65
   538.5 2079.13   578.1 2070.35   596.4 2067.76   602.8 2067.37   611.4 2068.68
   657.2 2086.56   706.7 2083.76   716.6  2084.3   726.4 2086.25   755.8 2094.88
     790 2107.67   804.7 2111.49   843.8 2130.27     883  2134.6     927 2145.75
#Mann= 3 , 0 , 0
       0      .1       0   596.4    .045       0   611.4      .1       0
Bank Sta=596.4,611.4
XS Rating Curve= 0 ,0
Exp/Cntr=0.3,0.1

Type RM Length L Ch R = 1 ,1182.8  ,68.6,69.5,70.3
XS GIS Cut Line= 4
     1874082.174      194193.569     1874398.735      194406.477
     1874659.267      194630.591      1874821.75      194714.634
#Sta/Elev= 30
       0 2291.17    34.7 2274.28    59.4 2260.67    79.3 2251.78    99.1 2241.57
   173.4 2207.96     213 2188.04   242.8 2175.96   292.3 2152.26   351.8 2131.72
   406.4 2111.67   431.3 2096.71   461.2 2077.07   491.1  2067.9   533.6 2063.59
   548.6 2062.36   550.8 2062.31   570.8  2064.6   605.6 2074.55   610.6 2075.09
   655.4 2077.68   725.2 2079.76   764.7 2083.72   774.6 2086.81   833.9 2111.65
   878.4 2128.02   888.3 2129.57   898.2 2127.36   903.2 2127.21   908.1 2128.57
#Mann= 3 , 0 , 0
       0      .1       0   533.6    .045       0   548.6      .1       0
Bank Sta=533.6,548.6
XS Rating Curve= 0 ,0
Exp/Cntr=0.3,0.1

Type RM Length L Ch R = 1 ,1113.4  ,63,62.3,61.7
XS GIS Cut Line= 3
     1874082.174      194249.598     1874351.111      194459.704
     1874726.501      194742.648
#Sta/Elev= 30
       0 2285.77    24.7 2274.61    54.4 2258.33   103.9 2232.81   163.2    2200
   202.8 2182.74   242.4 2163.08   267.1 2154.29   311.6 2130.87   336.3 2120.41
   351.2 2114.95   361.1 2109.06   380.9 2095.51   410.6 2072.78   425.4 2064.02
   440.2 2058.63   455.1  2055.3   468.1 2053.39   474.9 2053.22   483.1 2053.76
   509.5 2057.04   534.3 2063.12   578.8  2066.7   608.5 2071.38   643.1 2075.65
   687.6 2077.34     747 2083.45   761.9 2086.84   796.5 2098.48   811.4  2102.2
#Mann= 3 , 0 , 0
       0      .1       0   468.1    .045       0   483.1      .1       0
Bank Sta=468.1,483.1
XS Rating Curve= 0 ,0
Exp/Cntr=0.3,0.1

Type RM Length L Ch R = 1 ,1051    ,39.1,39.6,40
XS GIS Cut Line= 4
     1874036.935      194276.657     1874298.685      194505.688
     1874699.618      194774.194     1874897.388      194784.669
#Sta/Elev= 30
       0 2305.06    39.8 2281.15    94.4  2252.1   124.2 2234.07   173.9 2207.87
   238.5 2177.84   278.2 2160.87   367.7 2127.62   387.6 2113.92   427.4 2082.54
   447.3 2063.48   457.2 2055.64   467.2 2049.91   477.1 2048.33   492.1 2049.93
   492.1 2049.94   601.5 2064.06   656.2 2073.03   735.8 2077.17   765.7 2077.15
   775.6 2078.69   810.4 2090.75   835.3 2101.23   855.1  2104.7   889.8 2113.37
   919.5 2116.83   949.2 2142.12   973.9  2159.5   993.7 2170.96  1028.4 2187.31
#Mann= 3 , 0 , 0
       0      .1       0   477.1    .045       0   492.1      .1       0
Bank Sta=477.1,492.1
XS Rating Curve= 0 ,0
Exp/Cntr=0.3,0.1

Type RM Length L Ch R = 1 ,1011.5  ,247.2,243.3,239.3
XS GIS Cut Line= 4
     1873981.323      194356.052     1874250.259      194518.534
     1874670.473      194804.279     1874774.125      194851.904
#Sta/Elev= 30
       0 2298.62    34.9 2280.12   104.7 2246.26   169.6 2217.22   199.5 2203.14
   264.3 2167.34   289.3 2154.57   329.2 2138.85     369 2125.48     384 2115.52
   403.9 2100.24   458.7    2052   463.7 2049.49   468.6 2048.72   480.2 2049.35
   495.2 2050.49   543.4 2054.24   613.1 2062.34     653 2068.26   667.9 2069.53
   682.9 2072.97   692.8 2074.31   737.7 2077.66   762.6 2080.36   797.5 2086.84
   822.4 2089.98   857.1 2101.33   891.8 2106.14   926.5  2119.2   936.4 2123.82
#Mann= 3 , 0 , 0
       0      .1       0   480.2    .045       0   495.2      .1       0
Bank Sta=480.2,495.2
XS Rating Curve= 0 ,0
Exp/Cntr=0.3,0.1

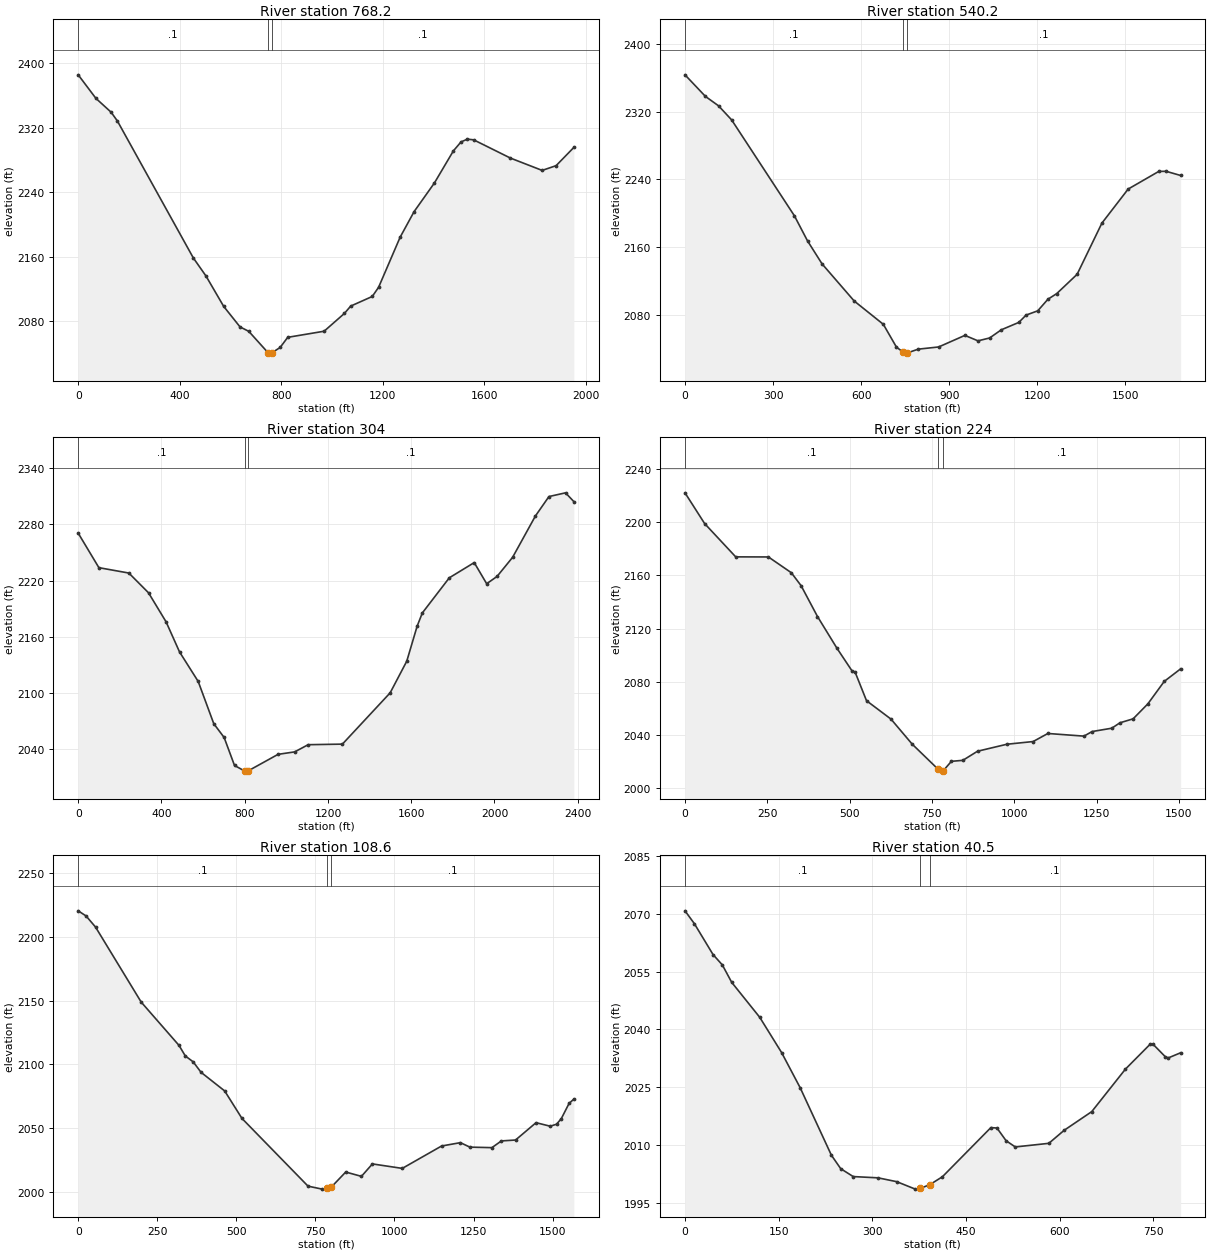
Type RM Length L Ch R = 1 ,768.2   ,228.1,227.9,227.8
XS GIS Cut Line= 4
     1873807.904      194346.185     1874208.709      194763.348
     1874572.704      194931.032     1875529.727      194746.989
#Sta/Elev= 30
       0 2385.58    69.8 2356.42   129.7 2339.26   154.6 2328.32   453.8 2158.64
   503.7 2136.24   573.5 2098.58   637.9 2073.13   672.5 2067.62   749.2 2040.87
   756.6 2040.63   764.2 2041.18   796.2 2047.67   825.9 2060.21   969.4 2067.78
  1049.2 2089.78  1074.2 2098.93  1159.2 2110.86  1184.2 2122.26  1269.1 2184.34
  1324.1 2216.02  1404.1 2251.49    1479 2291.33    1509 2302.38    1534 2305.85
    1559    2305  1703.9 2282.38  1828.9 2267.11  1883.9 2272.99  1953.8 2295.59
#Mann= 3 , 0 , 0
       0      .1       0   749.2    .045       0   764.2      .1       0
Bank Sta=749.2,764.2
XS Rating Curve= 0 ,0
Exp/Cntr=0.3,0.1

Type RM Length L Ch R = 1 ,540.2   ,235.5,236.2,236.9
XS GIS Cut Line= 4
     1873709.748      194505.688     1874069.654      194943.301
     1874523.626      195143.703     1875141.192      195041.457
#Sta/Elev= 30
       0 2363.62    69.6 2338.12   114.3 2326.98     159  2310.3   372.8 2196.96
   417.5 2167.27   467.2 2140.02   576.5 2096.22   675.8 2068.64   720.4 2041.75
   741.9 2036.05   755.2 2034.58   756.9 2034.78   794.9 2039.28   864.3 2041.87
   953.7 2055.56   998.3  2049.1    1038  2052.5  1077.7 2062.15  1137.4  2070.9
  1162.2 2079.56  1201.9 2084.58  1236.7 2098.32  1266.5 2104.92  1336.1 2127.77
  1420.5 2188.27    1510 2228.56  1614.3 2249.42  1639.1 2249.57  1688.8 2244.62
#Mann= 3 , 0 , 0
       0      .1       0   741.9    .045       0   756.9      .1       0
Bank Sta=741.9,756.9
XS Rating Curve= 0 ,0
Exp/Cntr=0.3,0.1

Type RM Length L Ch R = 1 ,304     ,80.4,80.1,79.8
XS GIS Cut Line= 4
     1873570.694      194669.282     1873828.354      195082.356
     1874323.249      195318.268     1875619.703      194955.571
#Sta/Elev= 30
       0 2270.63    99.4 2233.83   243.4 2228.09   337.8 2207.06   422.3 2176.04
   486.8 2144.02   576.6 2112.47   651.3  2067.5   701.2 2052.74     751  2022.9
   799.5 2017.04   810.8 2016.88   814.5  2016.9   960.3 2034.78  1040.1  2037.4
  1104.9 2045.06  1269.4 2045.68  1498.8 2100.37  1578.6 2134.11  1628.4  2171.4
  1653.4 2185.56    1783 2223.02  1902.7 2239.24  1962.5  2216.7  2012.4 2224.48
  2087.2 2244.88  2196.8 2288.97  2261.7 2309.66  2341.4 2313.63  2381.3 2304.28
#Mann= 3 , 0 , 0
       0      .1       0   799.5    .045       0   814.5      .1       0
Bank Sta=799.5,814.5
XS Rating Curve= 0 ,0
Exp/Cntr=0.3,0.1

Type RM Length L Ch R = 1 ,224     ,119.2,115.3,109.8
XS GIS Cut Line= 4
     1873505.571      194792.439     1873834.798      195177.573
      1874248.92      195368.706     1874785.155      195286.413
#Sta/Elev= 30
       0 2221.99    59.6 2198.91     154 2173.89   253.3 2173.82   322.9 2161.99
   352.7 2152.21   402.4 2129.07     462 2105.06   506.7 2088.45   516.6 2087.36
   551.3 2065.84   625.7 2052.01   690.1 2033.18   768.4 2014.44   779.3 2012.94
   783.4 2012.97   809.1  2020.3   843.8 2021.04   888.4 2027.88   977.7 2033.14
  1057.3 2035.16  1102.1 2041.22  1211.6 2039.23  1236.5 2042.68  1296.2 2045.18
  1321.1 2049.26    1361 2052.22  1405.7 2063.45  1455.5 2080.34  1505.3 2089.77
#Mann= 3 , 0 , 0
       0      .1       0   768.4    .045       0   783.4      .1       0
Bank Sta=768.4,783.4
XS Rating Curve= 0 ,0
Exp/Cntr=0.3,0.1

Type RM Length L Ch R = 1 ,108.6   ,71.1,68.1,66.4
XS GIS Cut Line= 5
     1873422.702      194837.257     1873789.011      195296.659
     1874208.332      195419.839      1874360.86      195375.133
     1874742.052      195333.672
#Sta/Elev= 30
       0  2220.5    24.9 2216.47    54.8 2207.76   199.2 2148.88   318.7 2114.92
   338.6 2106.64   363.5 2102.01   388.4 2093.79   463.1 2079.18   517.8  2057.6
   726.6 2004.47   771.3 2002.13   785.6 2002.71   800.6 2003.83   845.8 2015.54
   895.5 2012.15   930.2 2021.91  1024.6  2018.4  1148.8 2035.96  1208.4  2038.6
  1238.3 2035.08    1308 2034.68  1337.9 2039.95  1382.7 2040.66  1447.5 2054.27
  1492.3  2051.5  1512.2 2053.06  1527.2 2057.36    1552 2069.41    1567 2072.75
#Mann= 3 , 0 , 0
       0      .1       0   785.6    .045       0   800.6      .1       0
Bank Sta=785.6,800.6
XS Rating Curve= 0 ,0
Exp/Cntr=0.3,0.1

Type RM Length L Ch R = 1 ,40.5    ,49.3,40.5,32.1
XS GIS Cut Line= 5
     1873649.503      195234.439     1873958.503      195417.209
      1874054.49      195427.728      1874175.46      195443.507
     1874384.528      195389.597
#Sta/Elev= 30
       0  2070.8      15 2067.47    44.9 2059.45    59.8 2056.75    74.8 2052.23
   119.7 2043.15   154.6 2034.02   184.5 2024.84   234.4 2007.35   249.3 2003.86
   269.3 2001.81   309.1 2001.48   339.1 2000.48   368.7 1998.55   376.9 1998.76
   391.9 1999.71   412.1 2001.76   489.7 2014.52   499.5 2014.41   514.1 2011.11
   528.8  2009.5   582.5 2010.44     607 2013.82   651.2 2018.67   705.1  2029.7
   744.4 2036.12   749.3 2036.17   768.9 2032.93   773.8 2032.62   793.5 2033.95
#Mann= 3 , 0 , 0
       0      .1       0   376.9    .045       0   391.9      .1       0
Bank Sta=376.9,391.9
XS Rating Curve= 0 ,0
Exp/Cntr=0.3,0.1

Chan Stop Cuts=-1
Use User Specified Reach Order=0